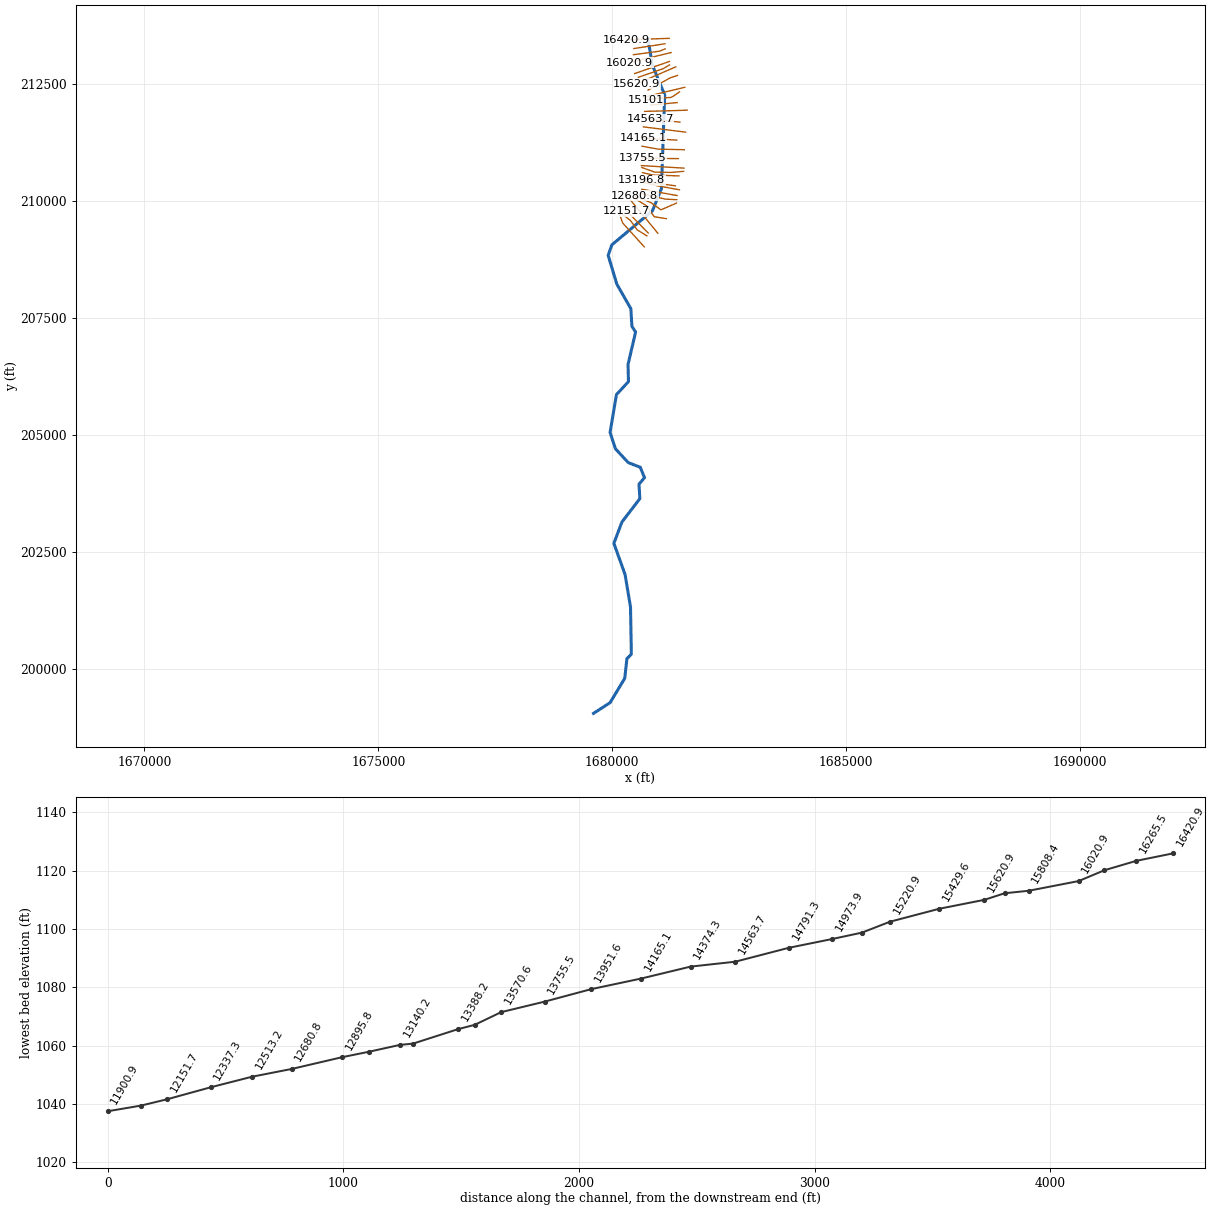
--- lmcrk.prj (project) ---

Proj Title=lmcrk
Current Plan=p01
Default Exp/Contr=0,0
English Units
Geom File=g01
Flow File=f01
Plan File=p01
BEGIN DESCRIPTION:
END DESCRIPTION:
DSS Export Rating Curves= 0
DSS Export Rating Curve Sorted= 0
DSS Export Volume Flow Curves= 0
DXF OffsetX= 0
DXF OffsetY= 0
DXF ScaleX= 0
DXF ScaleY= 0

--- lmcrk.p01 (plan) ---

Plan Title=Approximate Study - 100yr
Program Version=4.00
Geom File=g01
Flow File=f01
Subcritical Flow
K Sum by GR= 0
Std Step Tol= 0.01
Critical Tol= 0.01
Num of Std Step Trials= 20
Max Error Tol= 0.3
Flow Tol Ratio= 0.001
Split Flow NTrial= 30
Split Flow Tol= 0.02
Split Flow Ratio= 0.02
Log Output Level= 0
Friction Slope Method= 1
Unsteady Friction Slope Method= 2
Unsteady Bridges Friction Slope Method= 1
Parabolic Critical Depth
Global Vel Dist= 0 , 0 , 0
Global Log Level= 0
CheckData=True
Encroach Param=-1 ,0,0, 0
Run HTab= 0
Run UNet= 0
Run PostProcess= 0
Run WQNet= 0
UNET Theta= 0
UNET Theta Warmup= 0
UNET ZTol= 0
UNET ZSATol= 0
UNET MxIter= 0
UNET MaxInSteps= 0
UNET DtIC= 0
UNET DtMin= 0
UNET MaxCRTS= 0
UNET WFStab= 0
UNET SFStab= 0
UNET WFX= 1
UNET SFX= 1
UNET DSS MLevel= 1
UNET DZMax Abort= 0
UNET Convert EG Bridges= 0
UNET Use Existing IB Tables= 0
UNET Froude Reduction=False
UNET Froude Limit= 0
UNET Froude Power= 0
UNET Time Slicing=0,0, 5
Write IC File= 0
Echo Input=False
Echo Output=False
Write Detailed= 0
Detailed Automatic Start=False, 0
WQ ULTIMATE=-1
WQ Max Comp Step=1HOUR
WQ Output Interval=15MIN
WQ Output Selected Increments= 0
WQ Output face flow=0
WQ Output face velocity=0
WQ Output face area=0
WQ Output face dispersion=0
WQ Output cell volume=0
WQ Output cell surface area=0
WQ Output cell continuity=0
WQ Output face conc=0
WQ Output face dconc_dx=0
WQ Output face courant=0
WQ Output face peclet=0
WQ Output face adv mass=0
WQ Output face disp mass=0
WQ Output cell mass=0
WQ Output cell source sink temp=0
WQ Output cell source sink nsm=0
WQ Output MaxMinRange=-1
WQ Daily Max Min Mean=-1
WQ Daily Range=0
WQ Daily Time=0
WQ Create Restart=0
WQ Fixed Restart=0
WQ System Summary=False
Sorting and Armoring Iterations= 10
XS Update Threshold= 0.02
Hydraulics Update Threshold= 0.02
Energy Slope Method= 1
Volume Change Method= 0
XS Weighting Method= 0
Number of US Weighted Cross Sections= 1
Number of DS Weighted Cross Sections= 1
Upstream XS Weight=0.25
Main XS Weight=0.5
Downstream XS Weight=0.25
Number of DS XS's Weighted with US Boundary= 1
Upstream Boundary Weight= 1
Weight of XSs Associated with US Boundary= 0
Number of US XS's Weighted with DS Boundary= 1
Downstream Boundary Weight= 0.5
Weight of XSs Associated with DS Boundary= 0.5
Sediment Output Level= 4
Mass or Volume Output= 0
Output Increment Type= 1
Profile and TS Output Increment= 10
XS Output Flag= 0
XS Output Increment= 10
Disregard all LS=0
Disregard all Conn=0
Disregard all Breaches=0
Disregard all Pumps=0

--- lmcrk.f01 (steady flow) ---

Flow Title=USGS Regression Equation
Program Version=4.00
Number of Profiles= 1
Profile Names=P100yr
River Rch & RM=lmcrk,Main            ,16420.9
     493
River Rch & RM=lmcrk,Main            ,14973.9
     538
River Rch & RM=lmcrk,Main            ,13196.8
     595
River Rch & RM=lmcrk,Main            ,11900.9
     659
River Rch & RM=lmcrk,Main            ,9784
     717
River Rch & RM=lmcrk,Main            ,6808.5
     771
River Rch & RM=lmcrk,Main            ,6573.2
     985
River Rch & RM=lmcrk,Main            ,5623.7
    1043
River Rch & RM=lmcrk,Main            ,3830.3
    1102
River Rch & RM=lmcrk,Main            ,248.6
    1182
Boundary for River Rch & Prof#=lmcrk,Main            , 1
Up Type= 0
Dn Type= 3
Dn Slope=0.020656
DSS Import GetInterval= 0
DSS Import GetPeak= 0
DSS Import FillOption= 0

--- lmcrk.g01 (geometry) ---

Geom Title=USGS 3m DEM
Program Version=4.00

River Reach=lmcrk           ,Main
Reach XY= 30
     1680766.082      213466.916     1680857.491      212906.885
     1681123.788      212263.365     1681054.347       210262.85
     1680861.833      209787.305     1679994.486      209059.791
     1679915.007       208834.96     1680100.613      208218.608
     1680400.849      207694.011     1680422.546      207318.215
     1680501.965      207197.532     1680340.449       206505.24
     1680348.829      206135.766     1680092.644      205860.453
     1679955.754      205050.998     1680070.401      204702.969
     1680343.452      204406.594     1680600.833        204307.2
     1680692.923      204084.497     1680574.718      203947.374
     1680592.366      203634.999     1680209.846      203137.675
     1680037.079      202681.202     1680275.356      202018.257
     1680392.862      201318.822     1680411.144      200313.027
     1680316.092      200215.336     1680269.294      199794.809
     1679955.849      199276.053     1679601.523      199047.605

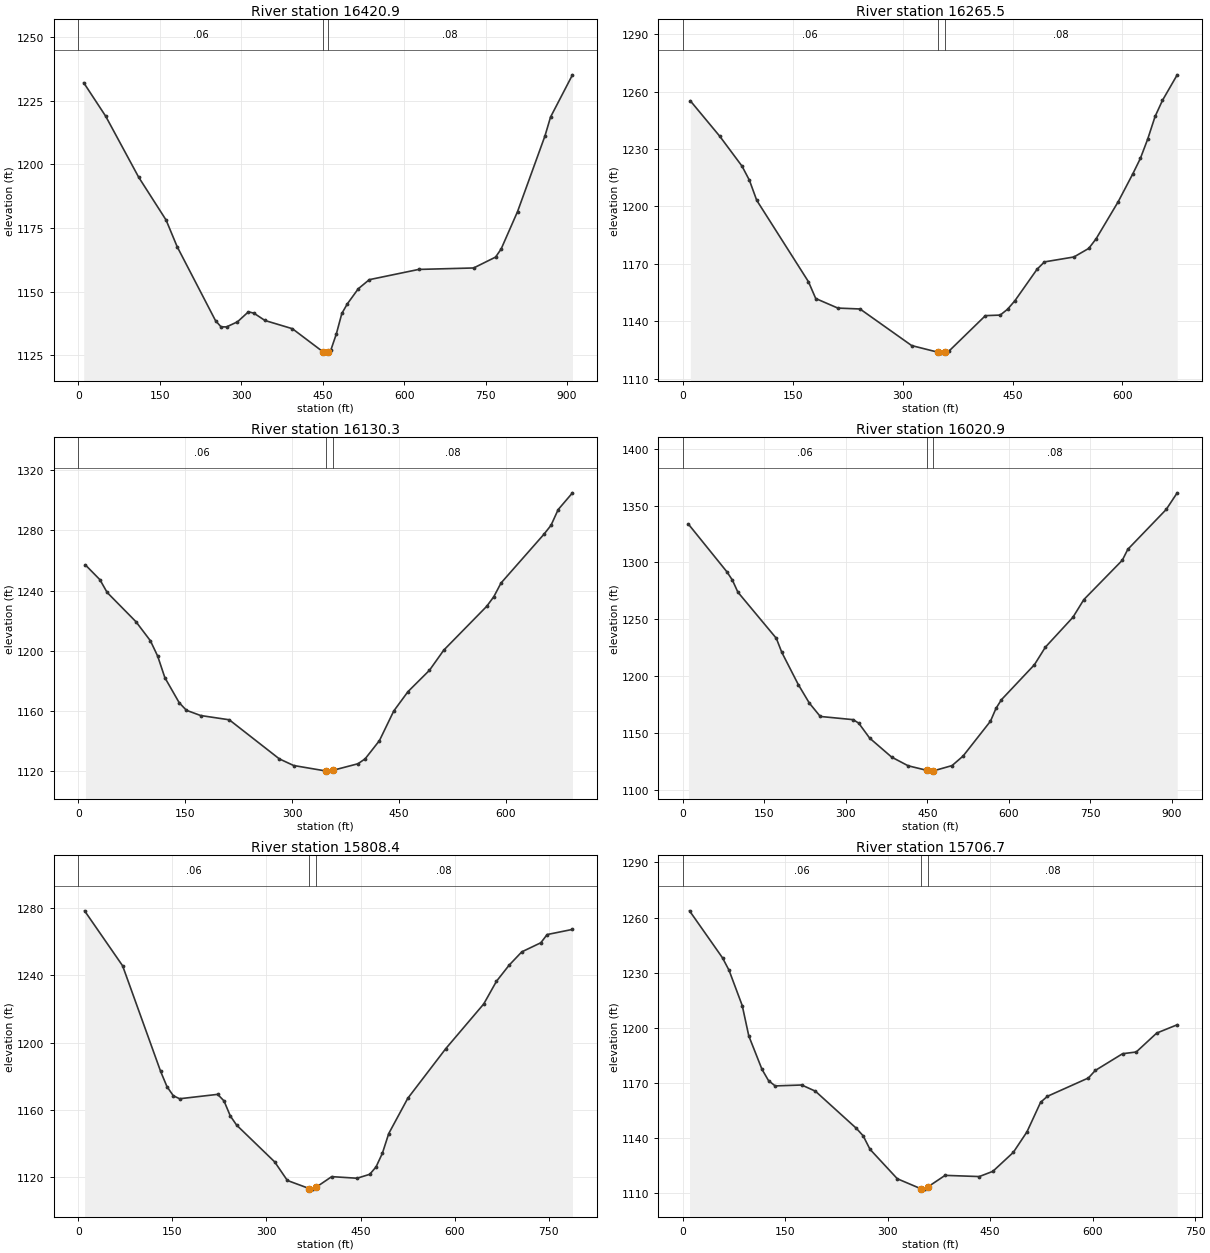
Type RM Length L Ch R = 1 ,16420.9 ,153,155.4,157.8
XS GIS Cut Line= 3
     1681221.159      213472.416     1680766.423      213456.922
     1680311.687      213441.428
#Sta/Elev= 30
    10.1    1232    50.6 1218.85   111.2 1194.96   161.8  1178.1     182 1167.72
   252.8 1138.62   262.9 1136.22     273 1136.19   293.2 1138.19   313.4 1142.13
   323.6 1141.55   343.8 1138.71   394.3 1135.48     450 1126.52     455  1125.9
     460  1126.5   465.1 1127.11   475.2 1133.43   485.3 1141.46   495.4 1145.22
   515.7 1151.19   535.9 1154.73   626.9 1158.75     728 1159.32   768.4 1163.59
   778.6 1166.76   808.9 1181.48   859.4 1211.19   869.6 1218.55     910 1235.12
#Mann= 3 , 0 , 0
       0     .06       0     450    .045       0     460     .08       0
Bank Sta=450,460
XS Rating Curve= 0 ,0
Exp/Cntr=0.3,0.1

Type RM Length L Ch R = 1 ,16265.5 ,135.6,135.2,134.9
XS GIS Cut Line= 2
     1681131.319      213356.719     1680464.224      213254.089
#Sta/Elev= 30
    10.1 1255.18    50.4 1236.61    80.6 1221.08    90.7 1213.72   100.7 1203.22
   171.3  1160.7   181.3 1151.88   211.5 1146.89   241.8 1146.42   312.3  1127.3
   347.6 1123.88   352.6 1123.35   357.6 1123.78   362.7 1124.21     413 1142.94
   433.2 1143.23   443.2 1146.27   453.3 1150.75   483.5 1167.17   493.6 1171.02
   533.9  1173.6   554.1 1178.07   564.1 1183.06   594.4 1202.52   614.5 1217.21
   624.6  1225.1   634.6 1235.18   644.7 1247.03   654.8 1255.44   674.9 1268.78
#Mann= 3 , 0 , 0
       0     .06       0   347.6    .045       0   357.6     .08       0
Bank Sta=347.6,357.6
XS Rating Curve= 0 ,0
Exp/Cntr=0.3,0.1

Type RM Length L Ch R = 1 ,16130.3 ,107.3,109.4,111.5
XS GIS Cut Line= 3
     1681134.393       213247.44      1681012.52      213197.729
     1680456.072       213122.36
#Sta/Elev= 30
    10.1 1256.94    30.4 1247.17    40.5 1238.72      81 1219.27   101.2 1206.64
   111.4 1196.44   121.5 1182.14   141.6 1165.53   151.7 1160.51   171.7 1157.03
   211.8  1154.2     282 1128.27   302.1 1123.86   347.2 1120.23   352.2 1120.13
   357.3 1120.68   392.3 1125.02   402.4  1128.3   422.4 1140.36   442.5 1160.02
   462.5 1172.91   492.6 1187.07   512.7 1200.45   572.8 1229.47   582.9 1235.92
   592.9 1244.93     653 1277.25   663.1 1283.29   673.1  1293.7   693.2 1304.83
#Mann= 3 , 0 , 0
       0     .06       0   347.2    .045       0   357.3     .08       0
Bank Sta=347.2,357.3
XS Rating Curve= 0 ,0
Exp/Cntr=0.3,0.1

Type RM Length L Ch R = 1 ,16020.9 ,210.6,212.5,214.5
XS GIS Cut Line= 3
     1681262.246      213168.643     1680820.033      213061.532
      1680377.82       212954.42
#Sta/Elev= 30
    10.1 1333.67    80.9 1291.77      91 1284.47   101.1 1273.88   171.9 1233.27
     182 1220.88   212.3 1192.61   232.6 1176.33   252.8 1164.52   313.4  1161.7
   323.6 1158.63   343.8 1145.45   384.2 1128.77   414.6 1121.12   449.9 1117.01
     455 1116.42   460.1 1116.51   495.4 1121.29   515.7 1129.66   566.2 1160.37
   576.3 1171.59   586.4 1179.28   647.1 1210.03   667.3  1225.5   717.9 1251.71
   738.1 1267.34   808.9 1301.94     819 1311.52   889.8 1346.66     910 1361.26
#Mann= 3 , 0 , 0
       0     .06       0   449.9    .045       0   460.1     .08       0
Bank Sta=449.9,460.1
XS Rating Curve= 0 ,0
Exp/Cntr=0.3,0.1

Type RM Length L Ch R = 1 ,15808.4 ,101.8,101.7,101.7
XS GIS Cut Line= 2
     1681225.397       212978.27     1680481.329      212719.557
#Sta/Elev= 30
    10.1 1278.39    70.7 1245.75   131.3 1183.02   141.4 1173.99   151.5 1168.57
   161.6 1166.77   222.2 1169.38   232.3 1165.51   242.4 1156.53   252.5 1151.09
   313.1 1129.27   333.3 1118.24   368.6 1113.38   373.7 1113.09   378.8 1114.13
     404 1120.51   444.4 1119.56   464.6 1121.89   474.7 1126.29   484.8 1134.42
   494.9  1146.1   525.2    1167   585.8 1196.53   646.4 1223.11   666.6 1236.54
   686.8 1246.11     707 1254.02   737.3 1259.42   747.4  1264.3   787.8 1267.36
#Mann= 3 , 0 , 0
       0     .06       0   368.6    .045       0   378.8     .08       0
Bank Sta=368.6,378.8
XS Rating Curve= 0 ,0
Exp/Cntr=0.3,0.1

Type RM Length L Ch R = 1 ,15706.7 ,84.2,85.8,87.3
XS GIS Cut Line= 3
     1681229.005      212905.875     1681087.889      212822.488
     1680558.702      212639.678
#Sta/Elev= 30
     9.6 1263.68    57.9  1238.1    67.5 1231.31    86.8 1212.12    96.4 1195.61
   115.7 1177.44   125.3 1171.29     135 1168.41   173.9  1168.9   193.9 1165.55
   253.9 1145.33   263.9 1141.24   273.9 1133.92   313.9 1117.89   348.8 1112.39
   353.9 1112.24     359 1113.54   383.9 1119.73   433.9 1119.08   453.8 1121.91
   483.8 1132.25   503.8 1143.42   523.8 1159.53   533.8 1162.76   593.8 1172.74
   603.8 1176.81   643.8 1185.93   663.8 1186.86   693.8 1197.17   723.8 1201.67
#Mann= 3 , 0 , 0
       0     .06       0   348.8    .045       0     359     .08       0
Bank Sta=348.8,359
XS Rating Curve= 0 ,0
Exp/Cntr=0.3,0.1

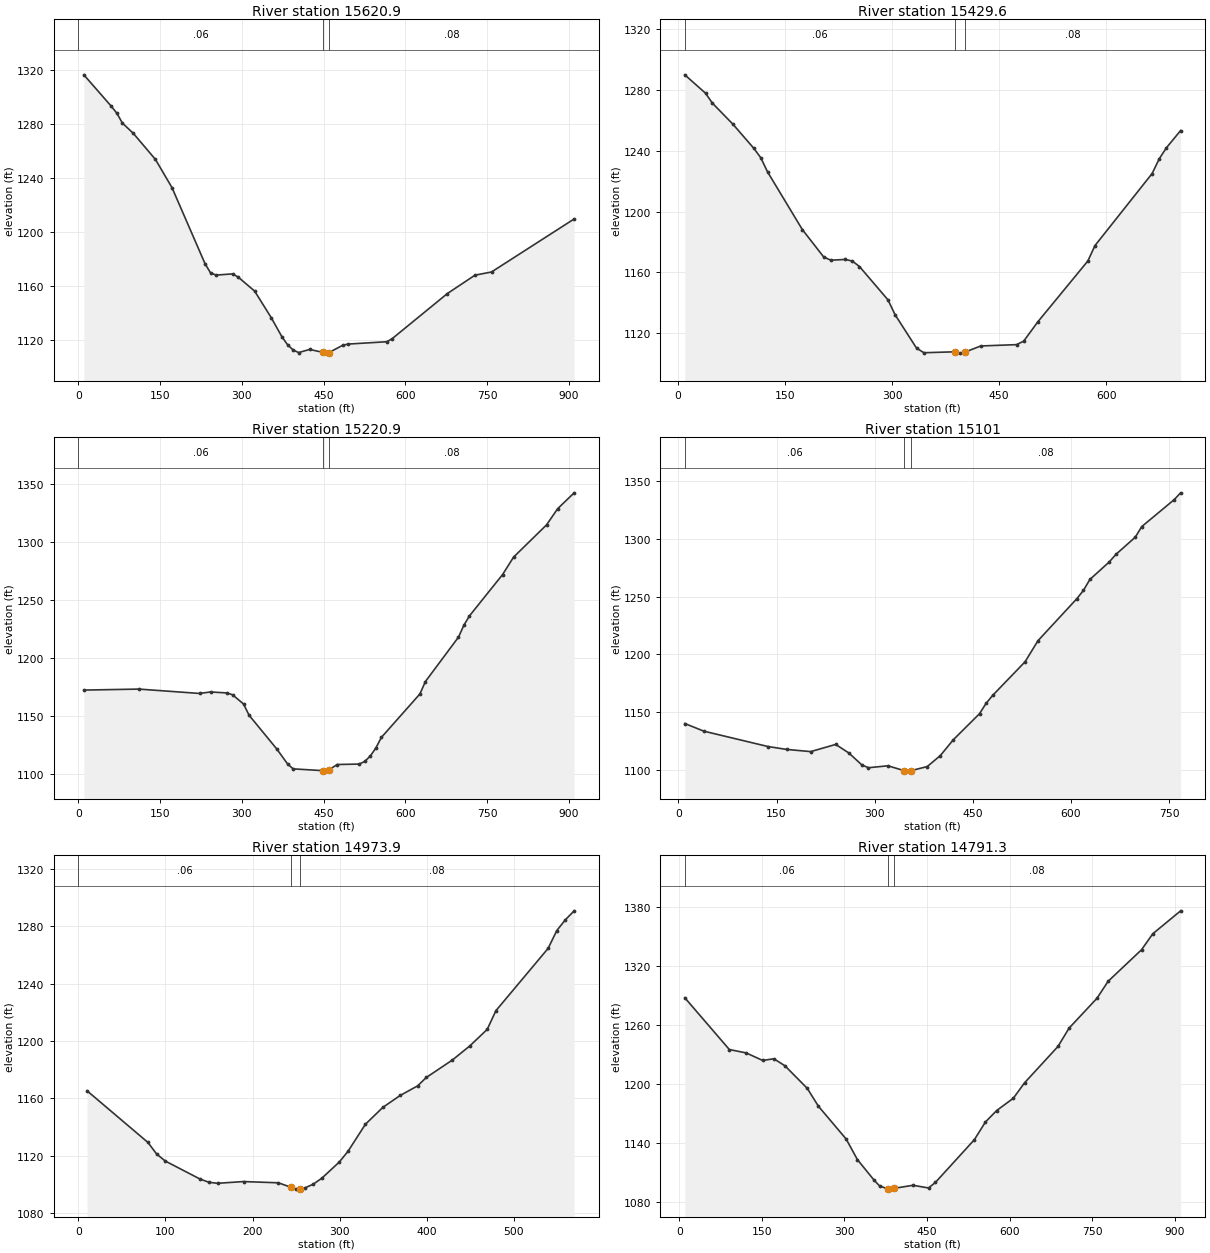
Type RM Length L Ch R = 1 ,15620.9 ,189.4,191.3,193.2
XS GIS Cut Line= 3
     1681361.086      212863.727     1680943.837      212682.265
     1680526.588      212500.804
#Sta/Elev= 30
    10.1 1316.22    60.7 1292.84    70.8 1287.71    80.9 1280.46   101.1 1272.77
   141.6 1253.49   171.9 1232.63   232.6 1176.21   242.7 1169.42   252.8 1167.82
   283.1  1168.7   293.2 1166.39   323.6 1155.96   353.9 1136.36   374.1 1121.79
   384.2 1116.12   394.3 1112.27   404.4 1110.41   424.7 1112.73   449.9 1110.46
     455 1109.99   460.1 1110.43   485.3 1115.84   495.4 1116.71   566.2 1118.43
   576.3  1120.8   677.4 1154.17     728 1167.77   758.3 1170.11     910 1209.42
#Mann= 3 , 0 , 0
       0     .06       0   449.9    .045       0   460.1     .08       0
Bank Sta=449.9,460.1
XS Rating Curve= 0 ,0
Exp/Cntr=0.3,0.1

Type RM Length L Ch R = 1 ,15429.6 ,214.1,208.7,203.4
XS GIS Cut Line= 3
     1681396.447      212678.933     1681240.364      212627.618
     1680767.838      212366.766
#Sta/Elev= 30
     9.7 1289.92    38.7 1277.85    48.3 1271.33    77.3 1257.35   106.3 1241.62
     116 1235.47   125.6 1226.08   174.3 1188.16   204.3  1170.1   214.3 1168.02
   234.3 1168.53   244.3 1167.46   254.3 1163.88   294.2 1141.95   304.2 1132.15
   334.2 1110.22  344.49 1107.19  387.79  1107.8  394.37 1106.93  401.67 1107.55
   424.2 1111.64   474.2 1112.51   484.2 1114.79   504.1 1127.54   574.1 1167.52
   584.1 1177.67   664.1 1225.03   674.1 1234.73   684.1 1241.95     704 1253.31
#Mann= 3 , 0 , 0
     9.7     .06       0  387.79    .045       0  401.67     .08       0
Bank Sta=387.79,401.67
XS Rating Curve= 0 ,0
Exp/Cntr=0.3,0.1

Type RM Length L Ch R = 1 ,15220.9 ,123.6,119.9,116
XS GIS Cut Line= 3
     1681552.789      212425.823     1681110.226      212320.176
     1680668.375       212211.53
#Sta/Elev= 30
    10.1 1172.37   111.2 1173.23   222.4 1169.47   242.7 1170.75     273 1169.91
   283.1 1168.31   303.3 1160.34   313.4 1150.67     364 1121.73   384.2 1108.59
   394.3 1104.45   449.8 1102.88     455  1102.5   460.2 1103.75   475.2  1108.2
   515.7 1108.59   525.8 1110.91   535.9 1115.55     546 1122.39   556.1 1131.53
   626.9 1169.04     637 1179.75   697.7 1218.02   707.8 1228.48   717.9 1236.38
   778.6 1271.95   798.8    1287   859.5  1314.9   879.7 1328.76     910 1342.44
#Mann= 3 , 0 , 0
       0     .06       0   449.8    .045       0   460.2     .08       0
Bank Sta=449.8,460.2
XS Rating Curve= 0 ,0
Exp/Cntr=0.3,0.1

Type RM Length L Ch R = 1 ,15101   ,126.2,127.1,128
XS GIS Cut Line= 5
      1681440.68      212328.581     1681312.392      212238.779
     1681256.266      212208.311     1680986.862      212195.482
     1680712.648      212153.789
#Sta/Elev= 30
     9.8    1140    39.1 1133.35     137 1120.05   165.7 1117.54   202.2 1115.66
   240.4 1121.89   260.4 1114.51   280.4 1104.11   290.4 1101.69   320.3 1103.37
   345.1 1099.14   350.3 1098.74   355.5 1099.15   380.3 1102.71   400.3 1112.22
   420.2 1125.98   460.2 1148.53   470.2 1157.48   480.2 1164.36   529.8 1193.55
   549.6 1211.86     609 1248.28   618.9 1255.34   628.8 1264.85   658.6 1280.16
   668.5 1286.54   698.2 1301.54   708.1 1310.72   757.6 1334.04   767.5 1339.98
#Mann= 3 , 0 , 0
     9.8     .06       0   345.1    .045       0   355.5     .08       0
#XS Ineff= 2 , 0
       0     320                       0
Permanent Ineff=
       F       F
Bank Sta=345.1,355.5
XS Rating Curve= 0 ,0
Exp/Cntr=0.3,0.1

Type RM Length L Ch R = 1 ,14973.9 ,184.9,182.7,179.8
XS GIS Cut Line= 2
     1681390.033        212099.5     1680823.429      212046.047
#Sta/Elev= 30
      10 1165.16    79.9 1129.12    89.9 1121.02    99.8 1116.14   139.8 1103.54
   149.8 1101.35   159.8 1100.61   189.7 1101.82   229.6 1100.95   244.4 1097.77
   249.6 1096.54   254.8 1096.93   259.6 1097.28   269.6 1099.97   279.6 1104.23
   299.5 1115.43   309.5  1122.9   329.5  1141.8   349.5 1153.59   369.4  1161.9
   389.4 1168.59   399.4 1174.45   429.3 1186.63   449.3 1196.46   469.3 1208.02
   479.3 1221.07   539.2 1264.54   549.2    1277   559.1 1284.56   569.1 1290.75
#Mann= 3 , 0 , 0
       0     .06       0   244.4    .045       0   254.8     .08       0
Bank Sta=244.4,254.8
XS Rating Curve= 0 ,0
Exp/Cntr=0.3,0.1

Type RM Length L Ch R = 1 ,14791.3 ,230.3,227.5,224.7
XS GIS Cut Line= 3
     1681603.703      211937.096       1681149.1      211922.739
     1680693.815      211911.458
#Sta/Elev= 30
    10.1 1288.13      91 1235.47   121.3 1232.08   151.6 1224.38   171.8  1226.1
     192 1218.93   232.5 1195.98   252.7 1177.83   303.2 1144.39   323.4 1123.63
   353.8 1102.66   363.9 1096.72   378.8 1093.79   384.1 1093.55   389.3 1094.28
   424.5 1097.46  452.56 1094.73     465  1100.3   535.8 1143.81     556 1161.87
   576.3 1173.45   606.6 1185.98   626.9  1201.6   687.6 1238.59   707.8 1257.26
   758.4 1287.58   778.7 1304.88   839.4 1336.99   859.7 1353.15   910.3 1376.51
#Mann= 3 , 0 , 0
    10.1     .06       0   378.8    .045       0   389.3     .08       0
Bank Sta=378.8,389.3
XS Rating Curve= 0 ,0
Exp/Cntr=0.3,0.1

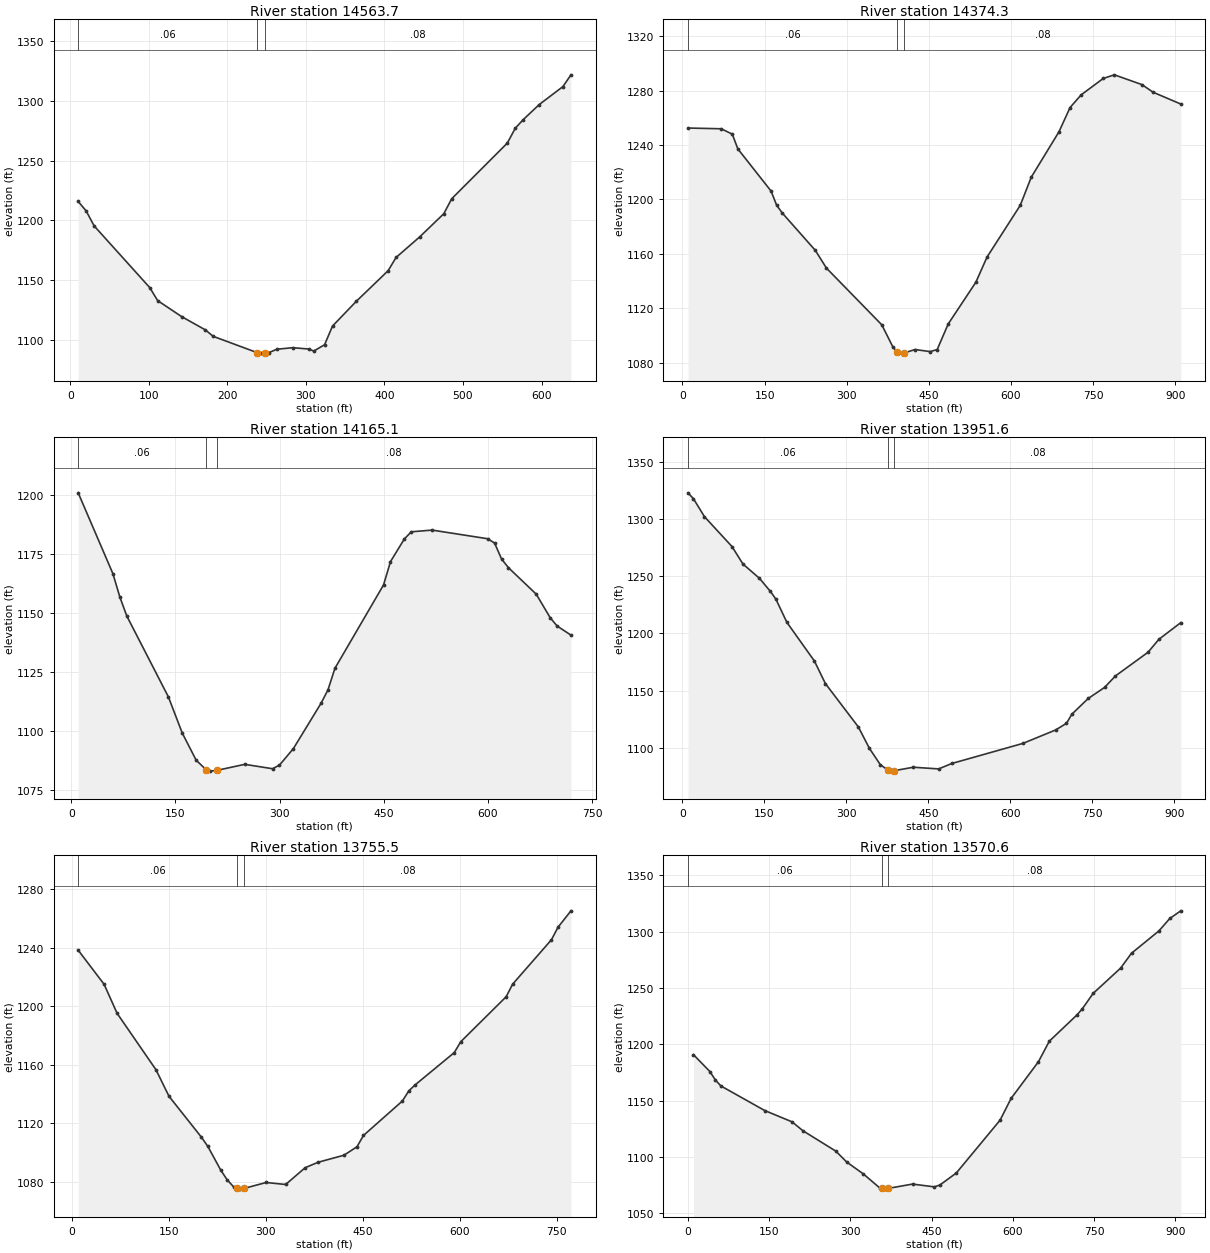
Type RM Length L Ch R = 1 ,14563.7 ,190.2,189.5,188.8
XS GIS Cut Line= 2
     1681447.762      211682.566     1680812.739      211738.157
#Sta/Elev= 30
    10.1 1215.73    20.2 1207.88    30.4 1195.29   101.2 1143.64   111.3 1132.74
   141.7  1119.4     172 1108.23   182.1 1102.81   237.6  1089.3   242.8 1088.78
   248.1 1089.01     253 1089.21   263.1 1092.04   283.3 1093.33   303.5 1092.22
  310.05 1090.52   323.8 1095.79   333.9 1111.42   364.3 1132.22   404.7 1157.75
   414.8 1168.83   445.2 1186.24   475.6 1205.47   485.7 1218.02   556.5  1264.6
   566.6 1276.99   576.7  1284.2     597 1296.78   627.3 1311.89   637.5 1321.72
#Mann= 3 , 0 , 0
    10.1     .06       0   237.6    .045       0   248.1     .08       0
Bank Sta=237.6,248.1
XS Rating Curve= 0 ,0
Exp/Cntr=0.3,0.1

Type RM Length L Ch R = 1 ,14374.3 ,207.9,209.2,210.5
XS GIS Cut Line= 3
     1681570.938      211468.368     1681119.377      211524.205
     1680667.816      211580.043
#Sta/Elev= 30
    10.1  1252.5    70.8 1251.95      91 1247.99   101.1 1237.18   161.8 1206.18
   171.9 1195.86     182 1190.17   242.7 1162.55   262.9 1149.58     364  1107.9
   384.2 1091.68  391.79 1088.04   394.3  1087.1   404.4 1087.18   424.7 1089.74
  452.25 1088.23   465.1 1089.69   485.3 1108.54   535.9 1139.26   556.1 1157.63
   616.8 1195.65     637 1216.42   687.6 1249.76   707.8 1267.57     728 1276.84
   768.4 1288.92   788.7 1291.59   839.2 1284.39   859.4  1278.8     910 1270.14
#Mann= 3 , 0 , 0
    10.1     .06       0  391.79    .045       0   404.4     .08       0
Bank Sta=391.79,404.4
XS Rating Curve= 0 ,0
Exp/Cntr=0.3,0.1

Type RM Length L Ch R = 1 ,14165.1 ,212.8,213.4,214
XS GIS Cut Line= 2
      1681381.48      211297.703      1680663.07      211340.466
#Sta/Elev= 30
      10 1201.01      60 1166.74      70 1156.86      80  1148.8   139.9 1114.51
   159.9 1099.16   179.9 1087.66   194.6 1083.53   199.9 1083.02   209.9 1083.35
   249.9  1085.9   289.9 1084.04   299.9 1085.57   319.9 1092.56   359.8 1111.79
   369.8 1117.51   379.8 1126.63   449.8 1161.97   459.8 1171.85   479.8 1181.48
   489.8 1184.49   519.8 1185.21   599.7 1181.55   609.7 1179.73   619.7 1172.99
   629.7 1169.26   669.7 1158.05   689.7 1148.11   699.7 1144.56   719.7 1140.69
#Mann= 3 , 0 , 0
      10     .06       0   194.6    .045       0   209.9     .08       0
Bank Sta=194.6,209.9
XS Rating Curve= 0 ,0
Exp/Cntr=0.3,0.1

Type RM Length L Ch R = 1 ,13951.6 ,195.9,196.1,196.4
XS GIS Cut Line= 3
      1681543.31      211092.209     1680980.448      211105.038
     1680637.628      211167.442
#Sta/Elev= 30
    10.1 1323.22    20.1 1318.04    40.2 1302.34    90.5 1276.18   110.6 1260.84
   140.8 1248.31   160.9  1236.8   170.9 1230.04     191  1209.7   241.3 1175.86
   261.4 1156.11   321.7 1118.08   341.8 1099.43   361.9 1085.02   376.7 1079.94
     382 1079.36   387.4 1079.75   422.3 1082.77  468.58  1081.3   492.6 1086.05
   622.7 1103.65   682.5 1115.41   702.4 1121.23   712.3 1129.27   742.2 1143.03
   772.1 1152.69     792 1162.77   851.7 1183.56   871.6 1194.94   911.5 1209.47
#Mann= 3 , 0 , 0
    10.1     .06       0   376.7    .045       0   387.4     .08       0
Bank Sta=376.7,387.4
XS Rating Curve= 0 ,0
Exp/Cntr=0.3,0.1

Type RM Length L Ch R = 1 ,13755.5 ,185.8,184.8,183.9
XS GIS Cut Line= 2
     1681413.552       210902.15     1680641.688      210910.702
#Sta/Elev= 30
      10 1238.23    50.1 1214.92    70.2  1195.1   130.3 1156.59   150.4  1138.5
   200.5 1110.59   210.5 1104.25   230.6 1087.97   240.6 1081.32   250.6 1076.55
   255.2 1075.89   260.6 1075.11     266 1075.54   300.7 1079.64   330.8 1078.27
   360.9 1089.72   380.9 1093.44     421 1098.27   441.1 1104.05   451.1 1111.75
   511.3 1135.27   521.3 1142.24   531.3 1146.39   591.5 1168.31   601.5 1175.72
   671.7 1206.43   681.7 1215.02   741.8 1245.37   751.9 1253.88   771.9 1265.08
#Mann= 3 , 0 , 0
      10     .06       0   255.2    .045       0     266     .08       0
Bank Sta=255.2,266
XS Rating Curve= 0 ,0
Exp/Cntr=0.3,0.1

Type RM Length L Ch R = 1 ,13570.6 ,112.2,113.3,114.3
XS GIS Cut Line= 3
     1681534.118        210699.1     1681079.923      210726.156
     1680625.728      210753.212
#Sta/Elev= 30
    10.1 1190.86    40.4  1175.9    50.6 1168.36    60.7 1163.12   141.6  1141.3
   192.1 1131.24   212.3 1123.31     273 1105.22   293.2  1095.5   323.6 1085.08
   353.9 1072.64   358.6 1072.11     364  1071.5   369.4 1072.13   414.6 1075.98
     455 1073.51   465.1 1075.15   495.4 1085.77   576.3 1132.72   596.6 1152.01
   647.1 1184.56   667.3 1202.88   717.9 1225.97     728 1231.48   748.2 1245.29
   798.8 1267.67     819 1280.91   869.6 1300.74   889.8 1311.83     910 1318.58
#Mann= 3 , 0 , 0
       0     .06       0   358.6    .045       0   369.4     .08       0
Bank Sta=358.6,369.4
XS Rating Curve= 0 ,0
Exp/Cntr=0.3,0.1

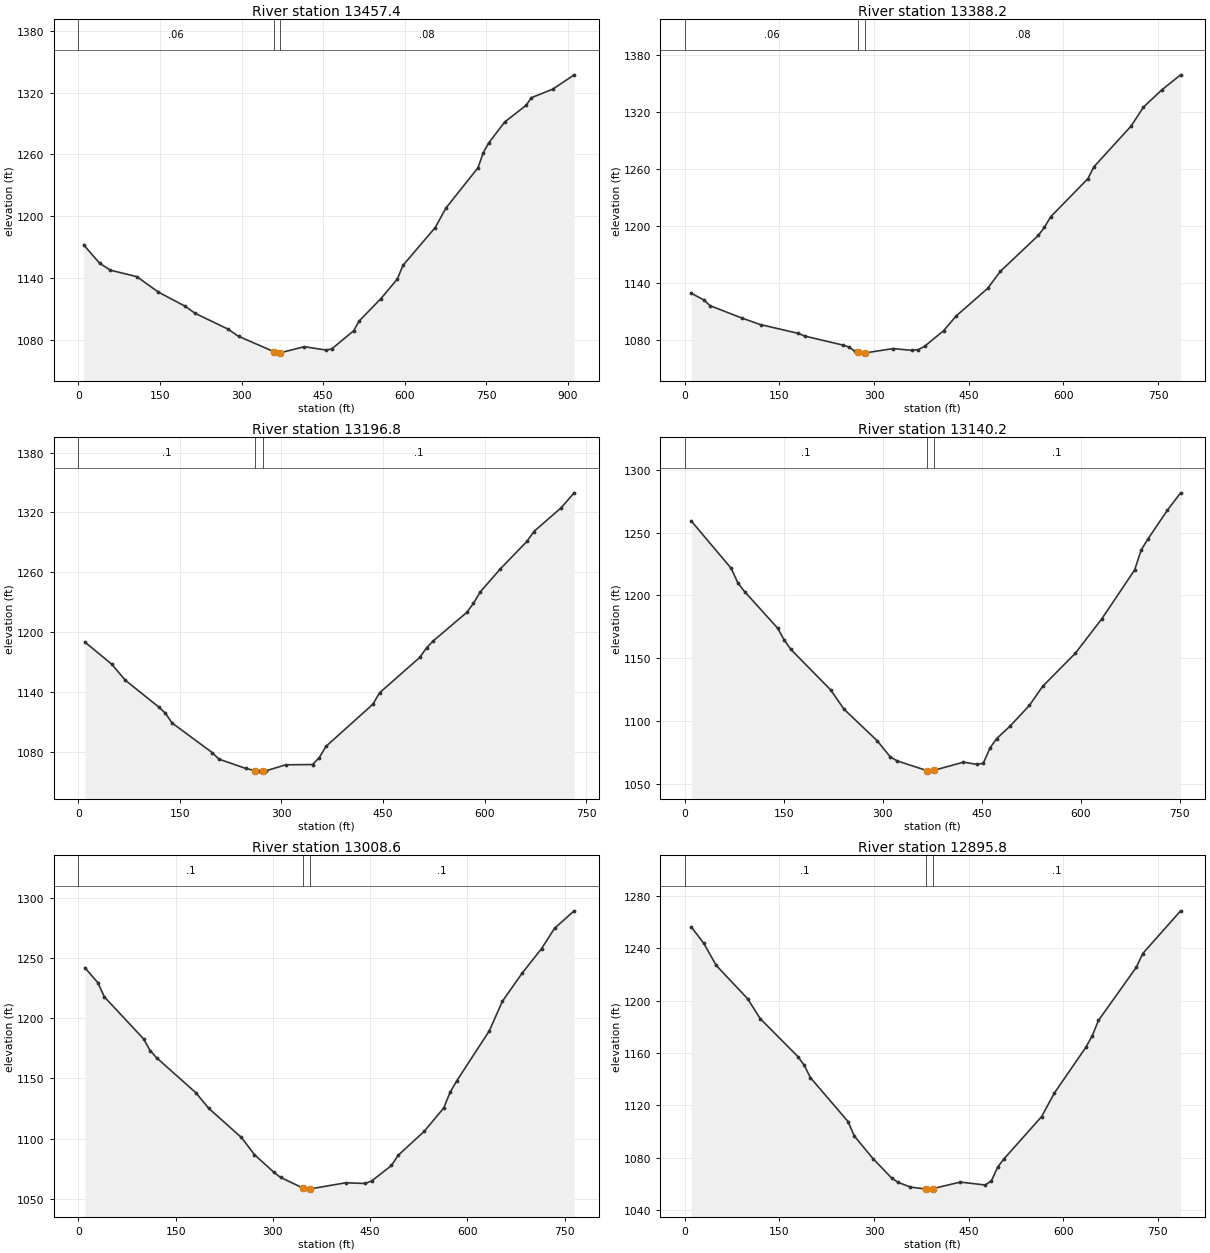
Type RM Length L Ch R = 1 ,13457.4 ,69.6,69.1,68.6
XS GIS Cut Line= 4
     1681528.877      210630.374     1681275.509      210607.923
     1680913.097      210612.734     1680635.675      210712.157
#Sta/Elev= 30
     9.8  1172.2    39.1 1154.39    58.7 1147.65   107.6 1141.33   146.7 1126.48
   195.7  1112.8   215.2 1105.62   274.5 1090.59   294.6 1083.41   359.7 1068.53
   365.1 1067.12   370.6 1067.37   415.4 1073.36   455.7 1070.07   465.8  1071.2
   506.1 1088.79   516.1 1098.21   556.4 1120.13   586.6  1139.1   596.7 1152.25
   656.1 1188.98   675.7 1207.86   734.7 1247.01   744.5 1261.71   754.3    1271
   783.8 1291.41   823.1 1307.55   832.9 1315.01   872.2 1323.28   911.5 1337.18
#Mann= 3 , 0 , 0
       0     .06       0   359.7    .045       0   370.6     .08       0
Bank Sta=359.7,370.6
XS Rating Curve= 0 ,0
Exp/Cntr=0.3,0.1

Type RM Length L Ch R = 1 ,13388.2 ,193.5,191.4,189.4
XS GIS Cut Line= 3
     1681427.851      210532.554     1680868.196      210551.797
     1680648.504      210603.113
#Sta/Elev= 30
      10 1128.77      30 1121.78      40 1115.66      90 1102.72     120  1095.7
     180 1086.47     190 1083.64     250 1074.24     260 1072.16     270 1067.48
   274.5 1066.67     280 1065.69   285.4 1065.88     330 1070.46     360 1068.62
     370 1069.38     380  1072.9     410 1089.27     430 1104.82     480 1133.95
     500  1151.8     560 1189.53   569.8 1198.14   579.6 1209.18   638.5 1249.21
   648.3 1261.92   707.1  1304.7   726.7 1324.71   756.2 1343.06   785.6 1358.68
#Mann= 3 , 0 , 0
       0     .06       0   274.5    .045       0   285.4     .08       0
Bank Sta=274.5,285.4
XS Rating Curve= 0 ,0
Exp/Cntr=0.3,0.1

Type RM Length L Ch R = 1 ,13196.8 ,57.5,56.6,55.7
XS GIS Cut Line= 3
     1681352.482       210320.88     1680980.448      210372.195
     1680629.261      210434.735
#Sta/Elev= 30
     9.9 1189.93    49.4 1167.89    69.2 1151.93   118.6 1125.08   128.5 1118.86
   138.4 1109.03   197.7  1079.3   207.5 1072.79   247.1 1063.46   261.4 1061.19
   266.8 1060.72   272.3 1060.86   276.7 1060.97   306.4 1067.09   345.9 1067.32
   355.8 1074.22   365.7 1085.49     435 1127.75   444.9  1139.2   504.4 1174.77
   514.3 1184.38   524.2 1191.24   573.7  1219.8   583.6 1228.89   593.5 1240.26
   623.3 1263.44   662.9 1291.19   672.8 1300.87   712.5 1324.31   732.3 1339.64
#Mann= 3 , 0 , 0
       0      .1       0   261.4    .045       0   272.3      .1       0
Bank Sta=261.4,272.3
XS Rating Curve= 0 ,0
Exp/Cntr=0.3,0.1

Type RM Length L Ch R = 1 ,13140.2 ,131.5,131.6,131.6
XS GIS Cut Line= 3
     1681439.076      210235.889     1680964.412      210322.483
     1680703.026      210385.024
#Sta/Elev= 30
    10.1 1259.08    70.4 1221.55    80.4    1210    90.5 1203.16   140.7 1174.02
   150.8  1164.4   160.8 1157.07   221.1 1124.84   241.2 1109.56   291.5 1084.47
   311.6 1071.46   321.7 1068.44   366.4 1060.73   371.9 1060.26   377.4 1060.88
   422.2  1067.4   442.3 1065.67   452.3 1066.52   462.4 1078.64   472.4 1086.06
   492.5 1095.87   522.3 1112.65   542.2 1127.69     592 1154.17   631.8 1181.39
   681.6 1220.32   691.5 1236.17   701.5 1244.73   731.4 1267.99   751.3 1281.68
#Mann= 3 , 0 , 0
       0      .1       0   366.4    .045       0   377.4      .1       0
Bank Sta=366.4,377.4
XS Rating Curve= 0 ,0
Exp/Cntr=0.3,0.1

Type RM Length L Ch R = 1 ,13008.6 ,114,112.9,111.8
XS GIS Cut Line= 2
     1681387.895      210113.181     1680635.274      210247.883
#Sta/Elev= 30
    10.1 1242.14    30.2 1229.59    40.2 1217.82   100.6 1182.91   110.7 1173.24
   120.7 1167.18   181.1 1138.18   201.2 1125.06   251.5 1100.88   271.6 1086.62
   301.8  1071.8   311.9 1067.63   346.6 1058.76   352.1 1057.91   357.6 1058.11
   412.5 1063.21   442.7 1062.61   452.7 1064.86   482.9 1077.57     493 1085.95
   533.2 1105.91   563.4 1125.35   573.4 1138.61   583.5 1147.95   633.8 1189.64
   653.9 1214.17   684.1 1237.36   714.3    1258   734.4 1274.91   764.6 1289.44
#Mann= 3 , 0 , 0
       0      .1       0   346.6    .045       0   357.6      .1       0
Bank Sta=346.6,357.6
XS Rating Curve= 0 ,0
Exp/Cntr=0.3,0.1

Type RM Length L Ch R = 1 ,12895.8 ,224.3,215,204.3
XS GIS Cut Line= 4
      1681382.95      210024.215     1681134.393      210037.043
     1680855.368      210102.791     1680611.621       210160.52
#Sta/Elev= 30
      10 1256.58    29.9 1244.06    49.8 1227.04    99.6 1201.56   119.5 1186.36
   179.2  1157.4   189.2 1150.84   199.1 1141.29   258.8 1107.69   268.7 1096.68
   298.3 1079.41     328  1064.5   337.9  1061.3   357.6 1057.63   381.7 1056.13
   387.3 1056.06   392.8  1056.4   436.7 1061.44   476.2 1059.23   486.1  1062.4
     496 1072.94   505.9 1079.15   565.6 1111.47   585.7 1129.37   635.8 1164.48
   645.8 1173.19   655.8 1185.01   715.9 1225.69   725.9 1236.09     786 1268.74
#Mann= 3 , 0 , 0
       0      .1       0   381.7    .045       0   392.8      .1       0
Bank Sta=381.7,392.8
XS Rating Curve= 0 ,0
Exp/Cntr=0.3,0.1

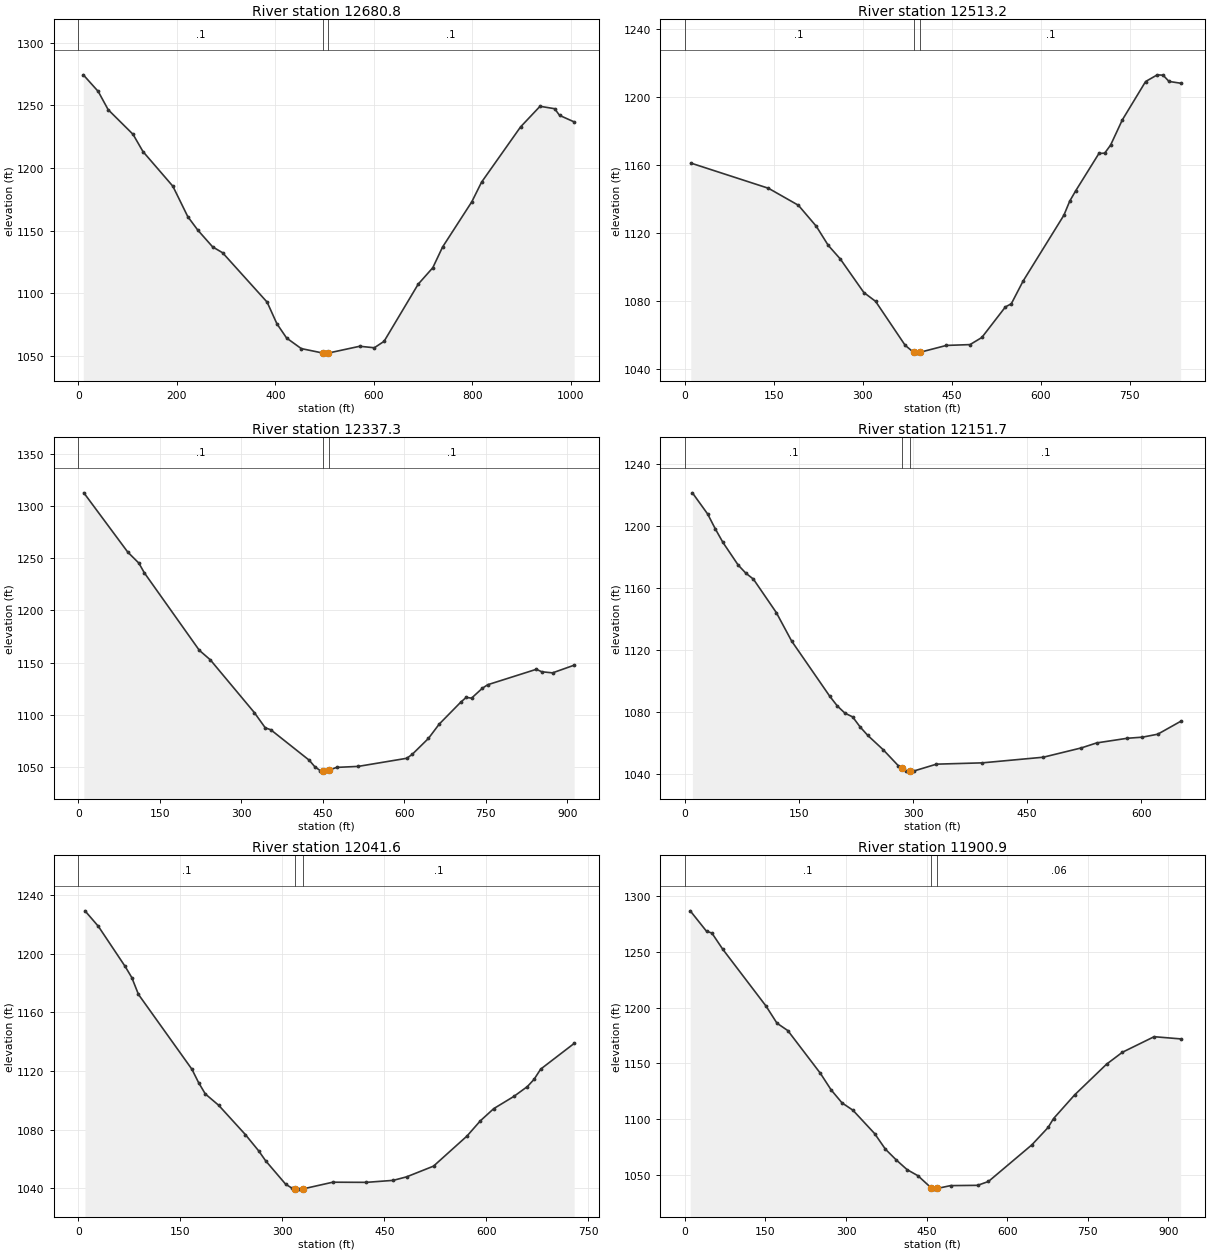
Type RM Length L Ch R = 1 ,12680.8 ,173.3,167.6,163.2
XS GIS Cut Line= 4
     1681376.989      209951.748     1681042.988      209807.729
     1680834.521      209958.467     1680480.777      210113.148
#Sta/Elev= 30
    10.1 1274.45    40.4 1261.16    60.6 1246.59   111.1  1226.9   131.3 1213.12
     192 1185.43   222.3 1161.12   242.5 1150.41   272.8 1136.93     293 1132.25
   383.5 1092.75   403.3  1075.5   423.1 1064.06   452.8 1055.64   496.7 1052.07
   502.3 1052.01   507.8 1052.07   571.5 1057.49   601.2  1056.3     621 1061.43
   690.3 1107.12     720 1120.29   739.8  1136.8   799.2 1172.97     819 1188.64
   898.2  1232.8   937.8  1249.3   967.5 1247.37   977.4 1242.07  1007.1 1236.82
#Mann= 3 , 0 , 0
       0      .1       0   496.7    .045       0   507.8      .1       0
Bank Sta=496.7,507.8
XS Rating Curve= 0 ,0
Exp/Cntr=0.3,0.1

Type RM Length L Ch R = 1 ,12513.2 ,174.4,175.9,177.4
XS GIS Cut Line= 4
     1681159.115      209619.274     1680900.402      209659.898
     1680733.628      209895.092      1680492.02      210046.899
#Sta/Elev= 30
    10.1 1161.08     141 1146.26   191.4 1136.27   221.6 1123.92   241.7 1112.71
   261.9 1104.76   301.7 1084.99   321.5 1079.79   371.2 1054.02   385.5 1049.83
   391.1 1049.36   396.7 1049.89   440.8 1053.89   480.6 1054.37   500.5 1058.55
   540.3 1076.54   550.2 1078.38   569.9 1091.62   638.8 1130.42   648.6 1138.69
   658.4 1144.61   697.8  1166.7   707.6 1166.93   717.5 1171.65   737.2 1186.41
   776.5 1209.01   796.2 1212.94     806 1212.71   815.9 1209.06   835.5 1208.01
#Mann= 3 , 0 , 0
       0      .1       0   385.5    .045       0   396.7      .1       0
Bank Sta=385.5,396.7
XS Rating Curve= 0 ,0
Exp/Cntr=0.3,0.1

Type RM Length L Ch R = 1 ,12337.3 ,184,185.6,187.3
XS GIS Cut Line= 3
     1680978.448      209306.315     1680689.134      209658.251
     1680397.536      210010.521
#Sta/Elev= 30
    10.1 1312.99    91.1 1256.02   111.4 1245.52   121.5 1236.19   222.7 1161.79
     243 1152.62     324    1102   344.2  1087.3   354.3 1085.47   425.2 1056.17
   435.3    1050   445.5 1046.18     450 1045.97   455.6 1045.73   461.2 1046.53
   475.5 1049.32   515.2 1050.27   604.7 1058.06   614.7 1061.82   644.5 1077.08
   664.4 1090.86   704.1 1111.95   714.1 1116.55     724 1115.83   743.9 1125.34
   753.8 1128.71   843.3 1143.52   853.2 1141.16   873.1 1140.09   912.9 1147.47
#Mann= 3 , 0 , 0
       0      .1       0     450    .045       0   461.2      .1       0
Bank Sta=450,461.2
XS Rating Curve= 0 ,0
Exp/Cntr=0.3,0.1

Type RM Length L Ch R = 1 ,12151.7 ,113.1,110,107
XS GIS Cut Line= 2
     1680772.114      209311.383     1680316.693      209777.495
#Sta/Elev= 30
      10 1221.22    30.1 1207.51    40.1 1197.96    50.1 1189.23    70.2 1174.57
    80.2 1169.39    90.2 1165.51   120.3 1143.93   140.4 1125.59   190.5 1089.96
   200.5 1083.65   210.5 1079.03   220.6 1076.61   230.6 1070.03   240.6 1064.62
   260.7 1055.46   280.7 1045.07   285.1 1043.55   290.7 1041.61   296.4 1041.63
   300.8 1041.65   330.8 1046.11     391 1046.95   471.2 1050.59   521.3 1056.61
   541.4 1059.82   581.5 1062.81   601.5 1063.53   621.6 1065.44   651.7 1073.73
#Mann= 3 , 0 , 0
       0      .1       0   285.1    .045       0   296.4      .1       0
Bank Sta=285.1,296.4
XS Rating Curve= 0 ,0
Exp/Cntr=0.3,0.1

Type RM Length L Ch R = 1 ,12041.6 ,138.5,140.8,143
XS GIS Cut Line= 4
     1680743.116      209251.282     1680534.648      209381.173
     1680390.325      209581.623     1680204.308       209727.55
#Sta/Elev= 30
     9.8 1229.18    29.5 1218.58    68.8 1191.29    78.6 1183.69    88.4  1172.2
     167 1121.19   176.8 1112.09   186.7 1104.35   206.3 1096.64   245.6 1076.64
   265.4 1065.41   275.3 1058.84   304.9 1042.78   314.8 1039.94     319 1039.73
   324.7 1039.46   330.3 1039.61   374.1 1044.18   423.5 1044.08     463 1045.44
   482.7 1047.84   522.2 1055.13   571.4 1075.64   591.1 1086.03   610.8 1094.35
   640.4 1102.68   660.1 1109.33   669.9 1114.21   679.8 1121.28     729 1138.78
#Mann= 3 , 0 , 0
       0      .1       0     319    .045       0   330.3      .1       0
Bank Sta=319,330.3
XS Rating Curve= 0 ,0
Exp/Cntr=0.3,0.1

Type RM Length L Ch R = 1 ,11900.9 ,167.8,166.9,166
XS GIS Cut Line= 3
     1680687.116      209016.324     1680226.892      209525.196
     1680144.177      209746.763
#Sta/Elev= 30
    10.1  1286.5    40.4 1268.23    50.4 1266.62    70.6 1252.16   151.3 1201.19
   171.5 1185.98   191.7 1179.36   252.2 1141.19   272.4 1126.24   292.6 1114.66
   312.8 1108.15   353.1 1087.29   373.3 1073.27   393.5 1063.62   413.7 1054.95
   433.9 1049.49   458.5 1038.64   464.1 1037.53   469.8 1038.13   494.4 1040.67
   544.9 1040.93     565 1044.37   645.8 1077.15     676 1092.68   686.1 1100.64
   725.5 1121.89   784.7 1149.27   814.2 1159.96   873.3 1173.89   922.6 1171.93
#Mann= 3 , 0 , 0
       0      .1       0   458.5    .045       0   469.8     .06       0
Bank Sta=458.5,469.8
XS Rating Curve= 0 ,0
Exp/Cntr=0.3,0.1