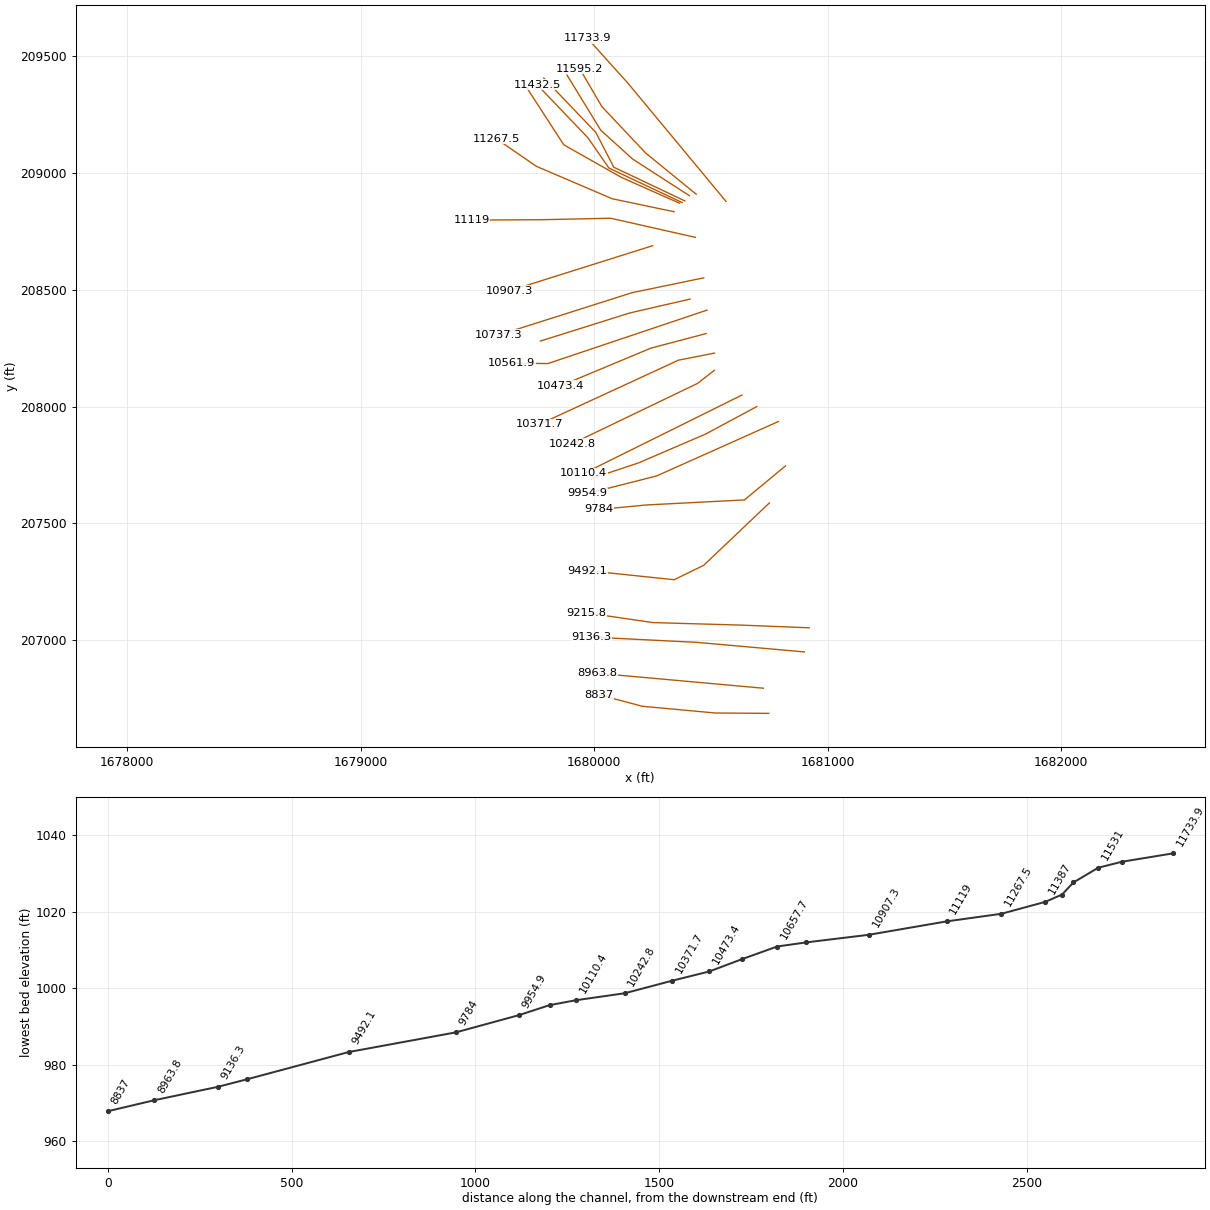
HEC-RAS study lmcrk.prj: lmcrk

--- lmcrk.g01 (geometry) --- (continued)

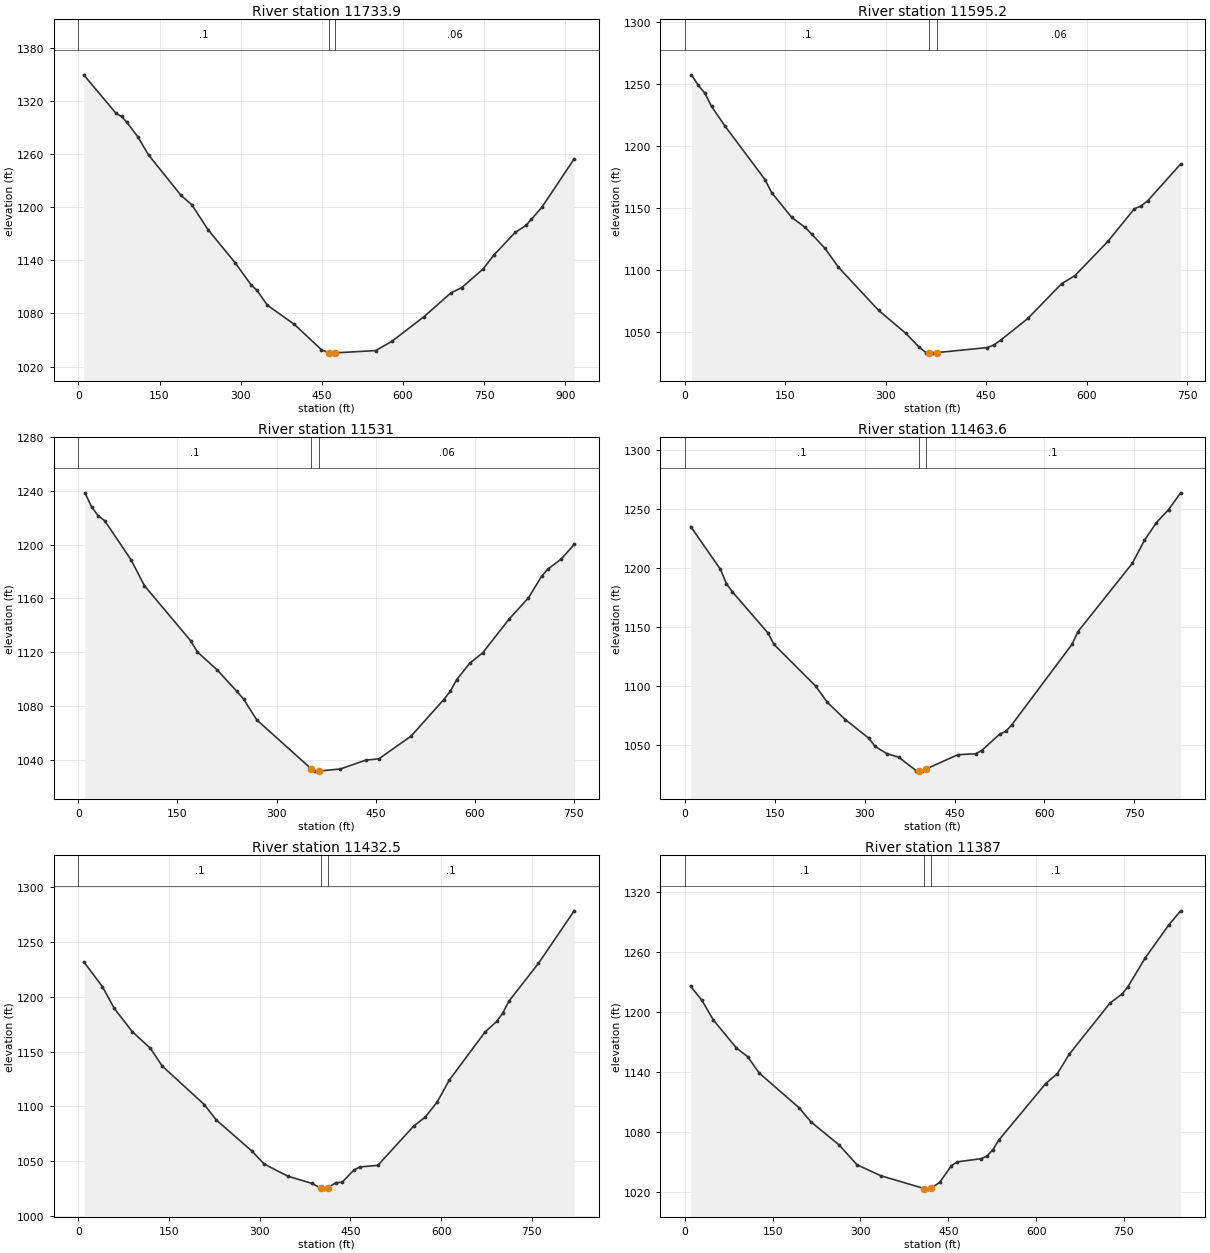
Type RM Length L Ch R = 1 ,11733.9 ,137.4,138.7,140.1
XS GIS Cut Line= 3
     1680564.762      208878.903     1680143.763      209385.924
      1679971.51      209576.907
#Sta/Elev= 30
      10 1349.76    69.9 1306.05    79.9 1302.67    89.9 1295.99   109.8 1279.78
   129.8 1259.18   189.7 1213.52   209.7 1202.93   239.6  1174.8   289.6 1137.49
   319.5 1112.15   329.5 1106.54   349.5 1089.32   399.4 1067.54   449.3    1039
   463.6 1035.23   469.3 1035.17     475 1035.48   549.2 1038.05   579.1 1048.37
   639.1 1076.55   688.7 1103.39   708.5 1109.22     748 1130.33   767.8 1146.04
   807.4 1171.73   827.2 1179.47   837.1  1186.4   856.9 1200.42   916.2 1254.71
#Mann= 3 , 0 , 0
       0      .1       0   463.6    .045       0     475     .06       0
Bank Sta=463.6,475
XS Rating Curve= 0 ,0
Exp/Cntr=0.3,0.1

Type RM Length L Ch R = 1 ,11595.2 ,62.6,64.2,65.8
XS GIS Cut Line= 4
     1680436.829      208909.716     1680220.344      209086.112
     1680032.723      209284.958     1679938.111      209446.921
#Sta/Elev= 30
      10 1257.39    19.9 1249.16    29.9 1242.64    39.9 1231.97    59.8 1216.23
   119.7 1172.96   129.7 1162.41   159.6 1142.42   179.5 1134.47   189.5 1128.96
   209.4 1117.38   229.4 1102.24   289.4 1067.44   329.9 1048.99   350.1 1037.62
   360.3 1033.45   364.7 1033.25   370.4 1032.99   376.1  1033.4   451.4 1037.46
   461.5 1039.55   471.6 1043.49   512.1 1060.94   562.5 1088.97   582.3 1095.44
   631.6 1123.07   671.1 1149.36     681 1151.59   690.9 1155.73   740.2 1185.47
#Mann= 3 , 0 , 0
       0      .1       0   364.7    .045       0   376.1     .06       0
Bank Sta=364.7,376.1
XS Rating Curve= 0 ,0
Exp/Cntr=0.3,0.1

Type RM Length L Ch R = 1 ,11531   ,74.3,67.4,60.5
XS GIS Cut Line= 4
     1680407.965      208903.302     1680164.218      209060.454
     1680027.912      209183.931     1679883.589       209419.66
#Sta/Elev= 30
      10 1238.68      20 1228.35      30 1221.53      40 1217.89      80 1188.62
     100 1169.54     170 1128.53     180 1120.28     210 1106.83     240 1090.78
     250 1085.12     270 1069.61     352 1033.32   357.8 1031.43   363.5 1031.47
   396.5 1033.03   435.2 1039.66   454.6 1040.56   503.5 1057.49   552.9 1084.68
   562.8 1090.82   572.6 1099.62   592.4  1111.8   612.1 1119.64   651.6 1144.54
   681.2 1160.51     701 1176.54   710.8 1182.02   730.6  1189.3   750.3 1200.24
#Mann= 3 , 0 , 0
       0      .1       0     352    .045       0   363.5     .06       0
Bank Sta=352,363.5
XS Rating Curve= 0 ,0
Exp/Cntr=0.3,0.1

Type RM Length L Ch R = 1 ,11463.6 ,27.8,31.1,34.4
XS GIS Cut Line= 4
     1680388.721      208880.852     1680084.038      209025.175
     1680007.066       209174.31     1679784.166      209406.831
#Sta/Elev= 30
     9.9  1235.3    59.5 1198.98    69.4 1186.78    79.3  1179.9   138.8  1144.9
   148.7 1135.23   218.1 1099.92     238 1085.91   267.7 1071.41   307.4 1055.34
   317.3 1048.62   337.1 1042.46   356.9  1039.4   386.5 1027.85   390.6 1027.75
   396.4 1027.59   402.1  1029.3   455.6 1041.57   485.2 1042.31   495.1 1045.07
   525.1 1058.97   535.2 1061.26   545.2 1066.75   645.9 1135.29   655.9 1146.13
   746.5 1204.07   766.7 1223.57   786.8 1238.72   806.9 1249.67   827.1 1263.95
#Mann= 3 , 0 , 0
       0      .1       0   390.6    .045       0   402.1      .1       0
Bank Sta=390.6,402.1
XS Rating Curve= 0 ,0
Exp/Cntr=0.3,0.1

Type RM Length L Ch R = 1 ,11432.5 ,37.3,45.5,53.7
XS GIS Cut Line= 4
     1680376.895      208873.836     1680062.991      209021.768
     1679972.789      209151.659     1679755.101      209378.968
#Sta/Elev= 30
     9.9 1231.32    39.7 1209.31    59.5 1189.36    89.2 1168.19     119 1153.03
   138.8 1136.76   208.2 1101.66     228 1087.63   287.5 1058.94   307.4 1047.32
     347 1036.14   386.5 1029.65   400.6 1025.38   406.3 1024.43   412.1 1025.63
   426.1 1030.43     436 1030.62   455.7 1041.91   465.6 1044.68   495.3 1046.17
   554.3 1081.83     574 1090.41   593.7 1104.21   613.3 1123.87   672.4 1167.74
     692 1177.67   701.9 1185.17   711.7 1195.78   760.9 1230.54   819.9 1278.46
#Mann= 3 , 0 , 0
       0      .1       0   400.6    .045       0   412.1      .1       0
Bank Sta=400.6,412.1
XS Rating Curve= 0 ,0
Exp/Cntr=0.3,0.1

Type RM Length L Ch R = 1 ,11387   ,117.1,119.4,121.8
XS GIS Cut Line= 4
      1680365.87      208870.929     1680115.709      208982.112
     1679869.825       209121.09     1679711.603      209364.837
#Sta/Elev= 30
     9.8 1225.97    29.3 1211.68    48.9  1191.9      88 1164.08   107.5  1155.2
   127.1 1138.85   195.5  1103.9   215.1 1090.09     264 1066.59   293.9 1047.02
   334.3 1036.05   409.2 1023.02     415 1022.52   420.7 1023.44   435.2 1029.29
   455.3 1045.98   465.4 1049.87   505.8    1053   515.8 1055.59   525.9 1061.81
     536 1071.47   616.3 1128.26   636.4 1138.39   656.4 1157.55   726.5 1209.18
   746.6 1217.93   756.6 1225.22   786.7 1254.55   826.8 1287.39   846.8 1301.41
#Mann= 3 , 0 , 0
       0      .1       0   409.2    .045       0   420.7      .1       0
Bank Sta=409.2,420.7
XS Rating Curve= 0 ,0
Exp/Cntr=0.3,0.1

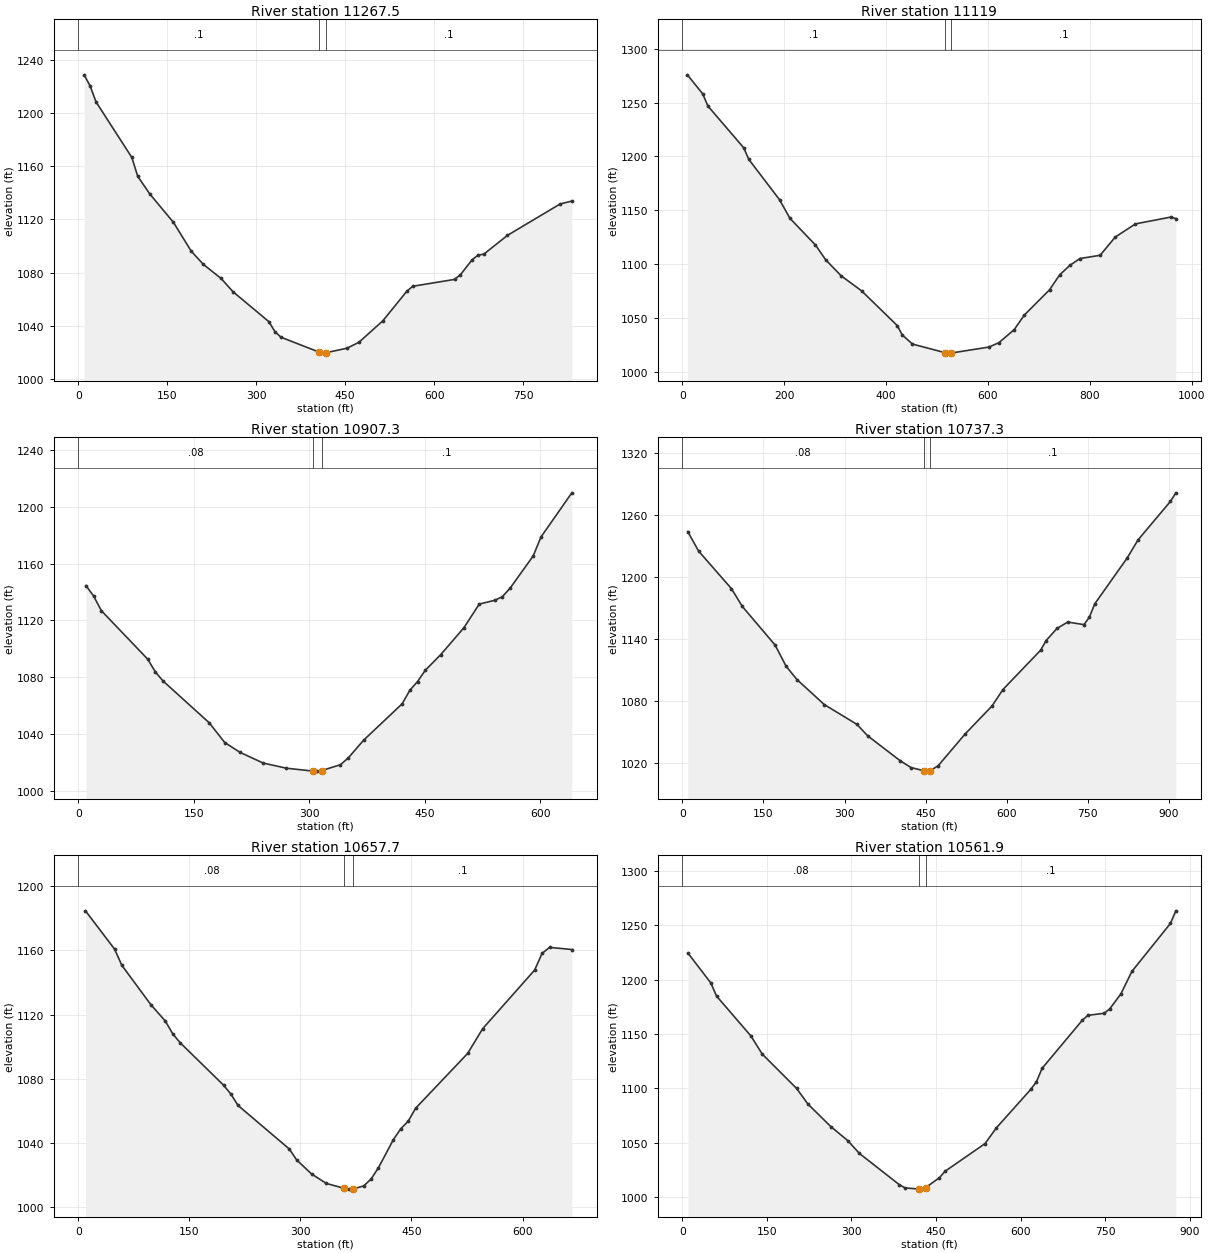
Type RM Length L Ch R = 1 ,11267.5 ,140.1,148.6,157.1
XS GIS Cut Line= 4
     1680342.351      208834.581     1680077.223      208890.172
     1679752.228      209029.151     1679581.178      209146.748
#Sta/Elev= 30
      10 1228.76    20.1 1220.34    30.1 1208.31    90.3 1166.65   100.3 1152.43
   120.4 1139.28   160.5 1117.76   190.6 1096.04   210.7 1086.25   240.8 1075.57
   260.9 1065.59   321.4 1043.05   331.5 1035.59   341.6  1031.4   406.5 1020.09
   412.3 1019.41   418.1 1019.78   452.7 1023.08   472.9  1027.5   513.3 1043.68
   553.7 1065.92   563.8 1069.71   634.2 1074.86   644.1 1078.34   663.9 1089.65
   673.8 1093.08   683.7  1093.9   723.2 1107.93   812.2 1131.62   831.9  1133.8
#Mann= 3 , 0 , 0
       0      .1       0   406.5    .045       0   418.1      .1       0
Bank Sta=406.5,418.1
XS Rating Curve= 0 ,0
Exp/Cntr=0.3,0.1

Type RM Length L Ch R = 1 ,11119   ,206,211.7,217.4
XS GIS Cut Line= 4
     1680433.811      208724.896     1680070.809      208806.786
     1679771.471      208800.371     1679474.004      208798.941
#Sta/Elev= 30
    10.1 1275.76    40.2  1258.1    50.3 1246.83   120.7    1208   130.7 1197.25
   191.1 1159.75   211.2 1142.68   261.5 1117.78   281.6 1104.05   311.8 1089.26
     352 1075.26     422 1043.04     432 1034.24     452 1025.83     516 1017.83
   521.8 1017.43   527.6 1017.51   601.7 1023.02   621.6  1027.1   651.6 1039.22
   671.5 1052.75   721.1 1076.27   740.9 1090.09   760.8 1098.83   780.6 1105.23
   820.3 1108.24     850 1125.16   889.7  1137.4   959.1 1143.72     969 1142.32
#Mann= 3 , 0 , 0
       0      .1       0     516    .045       0   527.6      .1       0
Bank Sta=516,527.6
XS Rating Curve= 0 ,0
Exp/Cntr=0.3,0.1

Type RM Length L Ch R = 1 ,10907.3 ,169.9,169.9,170
XS GIS Cut Line= 2
     1680250.411      208689.189     1679638.907      208496.757
#Sta/Elev= 30
      10 1144.51      20 1137.19    30.1 1126.82    90.2 1092.76   100.2 1083.74
   110.2 1077.36   170.3 1047.87   190.3 1034.05   210.4 1027.07   240.4 1019.58
   270.5 1015.98   304.7 1013.96   310.5 1013.93   316.4 1014.35   340.6 1018.45
   350.6 1023.13   370.6 1035.67   420.7  1061.3   430.7 1070.84   440.7 1076.99
   450.8 1084.92   470.8 1095.91   500.8 1114.76   520.9 1131.52   540.9 1134.14
   550.9 1136.73   560.9 1142.68     591 1165.43     601  1178.7   641.1  1209.8
#Mann= 3 , 0 , 0
       0     .08       0   304.7    .045       0   316.4      .1       0
Bank Sta=304.7,316.4
XS Rating Curve= 0 ,0
Exp/Cntr=0.3,0.1

Type RM Length L Ch R = 1 ,10737.3 ,79.7,79.6,79.5
XS GIS Cut Line= 3
     1680469.267      208551.565     1680162.748      208488.205
     1679591.267      208306.851
#Sta/Elev= 30
    10.1 1243.97    30.3 1225.03    90.9 1188.72   111.1  1171.4   171.6 1134.09
   191.8 1113.75     212 1100.69   262.5 1076.46     323 1057.23     343 1046.06
   402.9 1022.05   422.9 1015.42     447 1012.29   452.9 1011.95   458.8 1012.54
   472.9 1017.03   522.8 1047.82   572.8 1075.12   592.8 1090.93   662.7 1129.15
   672.7 1138.36   692.7  1150.1   712.7 1156.32   742.7 1153.84   752.7 1161.04
   762.7    1174   822.6 1218.38   842.6 1235.83   902.6 1273.21   912.6 1281.48
#Mann= 3 , 0 , 0
       0     .08       0     447    .045       0   458.8      .1       0
Bank Sta=447,458.8
XS Rating Curve= 0 ,0
Exp/Cntr=0.3,0.1

Type RM Length L Ch R = 1 ,10657.7 ,95.5,95.9,96.2
XS GIS Cut Line= 3
     1680411.172       208460.71     1680152.993      208401.377
     1679769.734      208281.107
#Sta/Elev= 30
     9.8 1184.79    49.1 1160.86    58.9 1150.75    98.1 1126.14   117.7 1115.87
   127.5 1108.04   137.4 1102.48   196.2 1075.88     206 1070.38   215.9 1063.15
     285 1035.98     295 1029.12   315.1 1020.35   335.2  1014.4   359.5 1011.34
   365.3 1010.87   371.2 1010.99   385.4 1012.85   395.5 1017.18   405.5 1024.28
   425.6  1041.8   435.6 1048.61   445.7 1053.36   455.7 1061.45     526 1095.72
   546.1 1111.08   616.4 1147.79   626.4 1158.16   636.5 1161.94   666.6 1160.62
#Mann= 3 , 0 , 0
       0     .08       0   359.5    .045       0   371.2      .1       0
Bank Sta=359.5,371.2
XS Rating Curve= 0 ,0
Exp/Cntr=0.3,0.1

Type RM Length L Ch R = 1 ,10561.9 ,87.1,88.5,89.9
XS GIS Cut Line= 3
     1680483.467       208413.37     1679801.405      208184.591
     1679645.321      208186.729
#Sta/Elev= 30
    10.1 1224.28    50.7 1196.86    60.8 1184.85   121.6 1148.29   141.9 1131.55
   202.7 1100.09   222.9 1085.67   263.4 1065.05   293.8 1052.02   314.1 1040.38
     385 1011.63   395.2  1008.7   419.7 1007.61   425.6 1007.56   431.5 1008.88
     456    1018   466.1 1023.94     537 1049.34   557.3  1063.9   618.1 1099.09
   628.2 1106.13   638.3  1118.5   709.3 1162.44   719.4 1167.12   748.7 1169.04
   758.4 1173.19   777.9 1186.73   797.5 1207.42   865.8 1251.47   875.5 1263.07
#Mann= 3 , 0 , 0
       0     .08       0   419.7    .045       0   431.5      .1       0
Bank Sta=419.7,431.5
XS Rating Curve= 0 ,0
Exp/Cntr=0.3,0.1

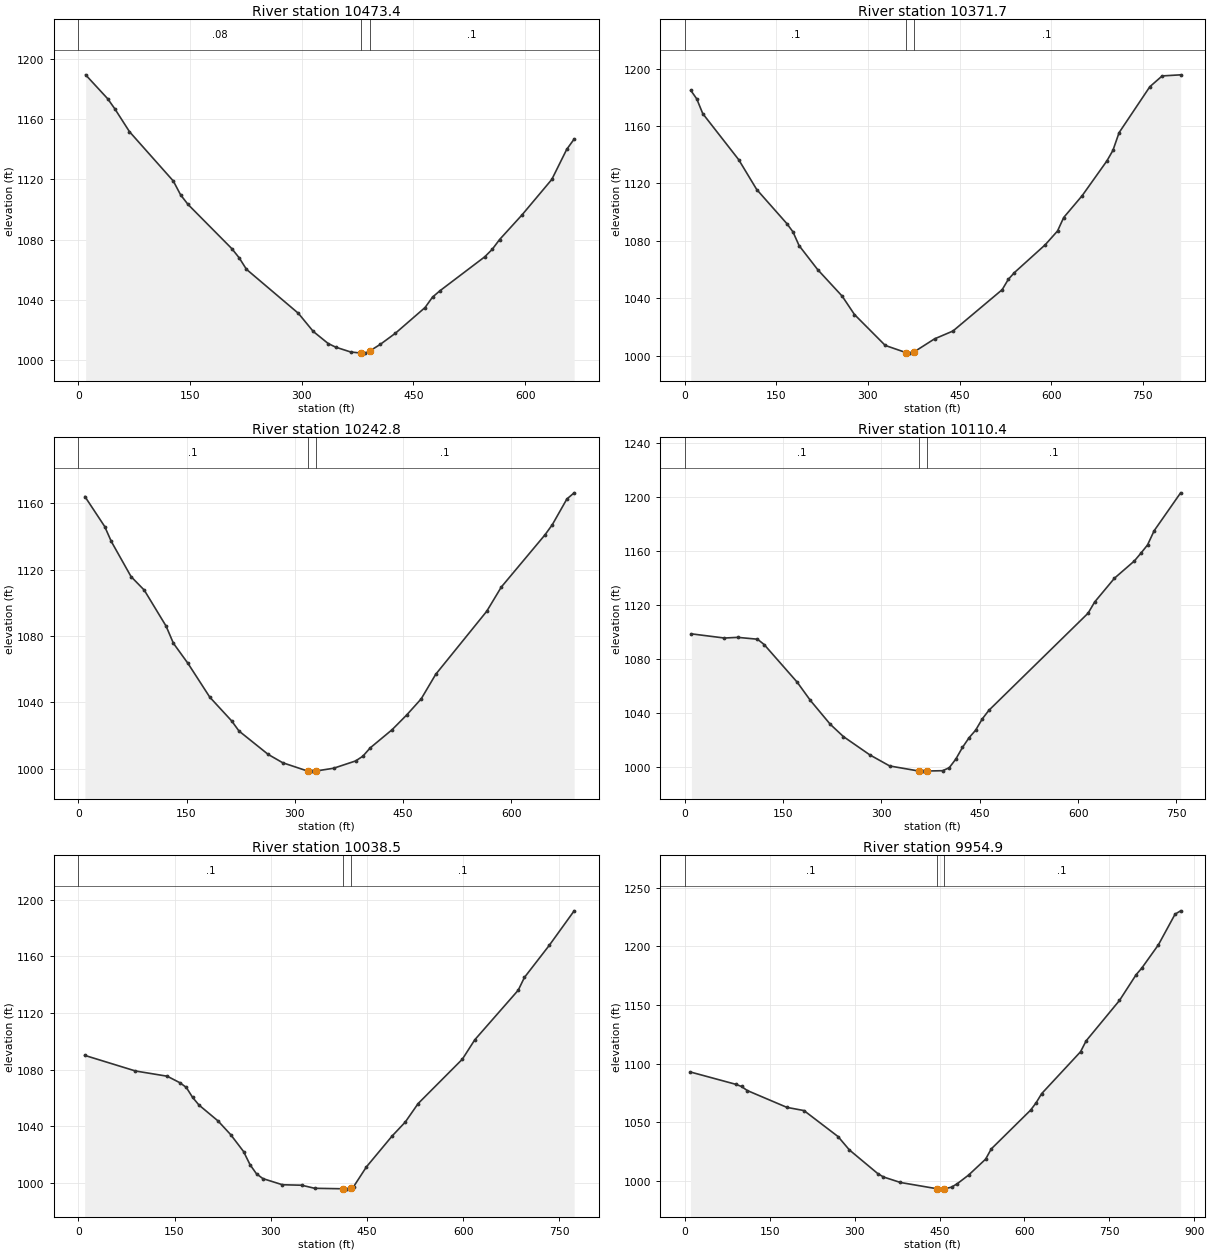
Type RM Length L Ch R = 1 ,10473.4 ,100.9,101.6,102.4
XS GIS Cut Line= 3
     1680480.126      208313.179     1680242.794      208250.639
     1679854.724      208088.676
#Sta/Elev= 30
     9.8 1189.71    39.3 1173.85    49.1 1167.01    68.7 1151.84   127.6 1118.96
   137.4 1109.72   147.3  1103.4   206.2 1073.91     216 1067.85   225.8 1060.18
   295.5 1030.88   315.5 1018.81   335.5 1010.77   345.6 1008.34   365.6 1005.15
   379.7 1004.37   385.6 1004.36   391.5 1005.81   405.6 1010.22   425.7 1017.55
   465.7 1034.74   475.7 1041.68   485.7 1045.91   545.8  1068.5   555.8 1073.46
   565.8 1080.03   595.9 1096.43   635.9 1120.06   655.9 1140.06   665.9 1146.94
#Mann= 3 , 0 , 0
       0     .08       0   379.7    .045       0   391.5      .1       0
Bank Sta=379.7,391.5
XS Rating Curve= 0 ,0
Exp/Cntr=0.3,0.1

Type RM Length L Ch R = 1 ,10371.7 ,128.6,128.9,129.3
XS GIS Cut Line= 3
     1680515.539      208229.492      1680361.46      208199.324
     1679766.526      207925.109
#Sta/Elev= 30
     9.8 1184.81    19.6 1178.88    29.4 1168.64    88.3 1136.56   117.8  1115.8
   167.1 1092.11   177.2 1086.32   187.2 1076.77   217.5 1060.13   257.8 1041.57
   277.9  1028.8   328.3 1007.29   362.7 1002.24   368.6 1001.93   374.6 1002.53
     409 1011.85   439.2 1017.31   519.8 1046.08   529.9 1053.29     540 1058.04
   590.4 1077.38   610.5 1086.96   620.6 1096.32   650.8  1111.5   691.2 1135.63
   701.2 1143.02   711.3 1155.38   761.7 1187.37   781.9 1194.87   812.1 1195.63
#Mann= 3 , 0 , 0
       0      .1       0   362.7    .045       0   374.6      .1       0
Bank Sta=362.7,374.6
XS Rating Curve= 0 ,0
Exp/Cntr=0.3,0.1

Type RM Length L Ch R = 1 ,10242.8 ,132.3,132.4,132.6
XS GIS Cut Line= 3
     1680515.405      208156.027     1680443.244      208099.901
     1679906.039      207841.722
#Sta/Elev= 30
     9.1 1164.03    36.6 1145.93    45.7 1136.97    73.1  1115.8    91.4 1107.65
   121.7 1085.96   131.8 1075.67     152 1063.54   182.3 1043.17   212.6 1028.89
   222.7 1022.83   263.2 1008.73   283.4  1003.7   317.8  998.72   323.8  998.66
   329.7  998.74   354.1 1000.42   384.4 1004.79   394.5 1007.66   404.6 1012.64
   434.9 1023.57   455.1 1032.41   475.3 1042.15   495.5 1056.98   566.2 1094.93
   586.4 1109.51     647 1140.98   657.1 1147.06   677.3 1162.53   687.4 1166.25
#Mann= 3 , 0 , 0
       0      .1       0   317.8    .045       0   329.7      .1       0
Bank Sta=317.8,329.7
XS Rating Curve= 0 ,0
Exp/Cntr=0.3,0.1

Type RM Length L Ch R = 1 ,10110.4 ,72.9,71.9,70.8
XS GIS Cut Line= 2
     1680633.136      208049.889      1679955.35      207714.203
#Sta/Elev= 30
    10.1 1098.47    60.5 1095.38    80.7 1095.88   110.9 1094.51     121 1090.59
   171.4 1062.73   191.6 1049.18   221.9 1031.54     242 1022.41   282.4 1008.84
   312.6 1000.67   357.1  996.91   363.1  996.85     369  996.92   393.3  997.17
   403.4  999.36   413.5  1005.8   423.6 1014.41   433.6 1021.53   443.7 1027.17
   453.8 1035.51   463.9 1041.88   615.2 1113.76   625.3 1122.08   655.5 1139.68
   685.8 1152.43   695.9 1158.25   705.9 1164.28     716 1174.81   756.4 1202.88
#Mann= 3 , 0 , 0
       0      .1       0   357.1    .045       0     369      .1       0
Bank Sta=357.1,369
XS Rating Curve= 0 ,0
Exp/Cntr=0.3,0.1

Type RM Length L Ch R = 1 ,10038.5 ,83.3,83.6,83.9
XS GIS Cut Line= 4
     1680696.612      208000.478     1680478.523      207883.416
     1680191.479      207759.939     1679989.426      207692.588
#Sta/Elev= 30
     9.9 1090.03    89.1 1078.99   138.6  1075.3   158.4 1070.69   168.3 1067.39
   178.2 1060.32   188.1 1054.94   217.8 1043.72   237.6    1034   257.6 1022.11
   267.7 1012.81   277.8 1006.35   287.8 1002.98   318.1  998.66   348.3  998.31
   368.5  996.15   412.9   995.8   418.9  995.56   424.8  996.52     429   997.2
   449.1 1011.24   489.4 1033.18   509.6 1042.87   529.8 1056.01   598.7 1087.33
   618.1 1101.04   685.8 1136.05   695.5 1145.08   734.3 1167.79     773  1192.1
#Mann= 3 , 0 , 0
       0      .1       0   412.9    .045       0   424.8      .1       0
Bank Sta=412.9,424.8
XS Rating Curve= 0 ,0
Exp/Cntr=0.3,0.1

Type RM Length L Ch R = 1 ,9954.9  ,178.4,170.9,163.5
XS GIS Cut Line= 3
     1680789.219      207936.568     1680267.516      207703.512
     1679972.455      207628.678
#Sta/Elev= 30
      10 1092.82    90.2 1082.32   100.2 1080.47   110.3 1077.04   180.4 1062.66
   210.5 1059.94   270.7 1037.77   290.7 1026.38   340.8 1006.22   350.9  1003.3
   380.9  998.61   445.1   993.3   451.1  992.94   457.1  993.01   471.1  994.62
   481.2  997.53   501.2  1004.9   531.3 1018.48   541.3 1027.21   610.7 1060.25
   620.5 1066.54   630.3 1074.37     699 1110.08   708.9  1119.4   767.8 1153.86
   797.2 1175.81   807.1 1181.39   836.5 1201.27     866 1227.44   875.8 1230.29
#Mann= 3 , 0 , 0
       0      .1       0   445.1    .045       0   457.1      .1       0
Bank Sta=445.1,457.1
XS Rating Curve= 0 ,0
Exp/Cntr=0.3,0.1

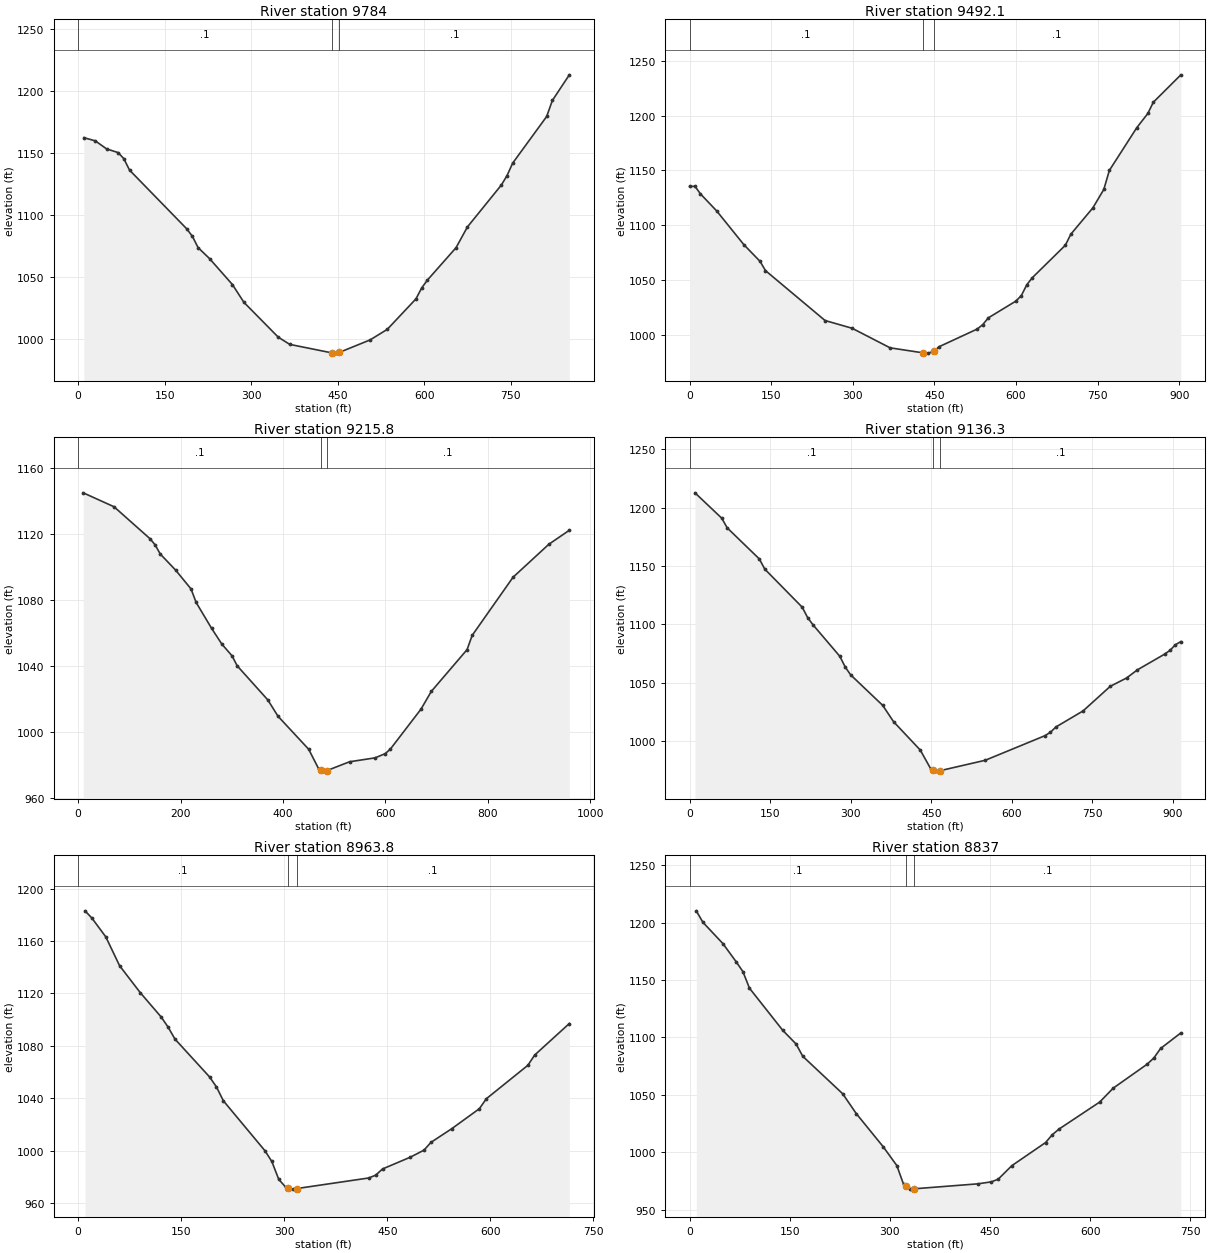
Type RM Length L Ch R = 1 ,9784    ,283.7,291.8,299.9
XS GIS Cut Line= 4
     1680819.153      207746.275     1680643.827      207600.882
     1680226.892      207579.501     1680021.632      207560.258
#Sta/Elev= 30
     9.9 1162.44    29.7 1159.91    49.5 1153.35    69.3 1150.42    79.2 1145.52
    89.1 1136.28   188.2 1088.88   198.1 1082.77     208 1073.65   227.8 1064.81
   267.5 1043.81   287.4 1029.47     347  1001.3   366.9  995.51   440.4   988.6
   446.4  988.46   452.5     989   506.1  999.14   535.9 1007.68   585.6 1032.31
   595.6 1041.18   605.5  1047.5   655.1 1073.65   674.7 1090.33   733.6 1124.23
   743.4 1131.82   753.2 1141.91   812.1 1179.55     822 1192.52   851.4  1213.2
#Mann= 3 , 0 , 0
       0      .1       0   440.4    .045       0   452.5      .1       0
Bank Sta=440.4,452.5
XS Rating Curve= 0 ,0
Exp/Cntr=0.3,0.1

Type RM Length L Ch R = 1 ,9492.1  ,286.2,276.4,266.5
XS GIS Cut Line= 4
     1680750.733      207588.054     1680468.895      207320.853
      1680342.67      207259.318     1679970.592      207298.184
#Sta/Elev= 30
       0 1135.49      10 1135.49    19.9 1128.64    49.8 1113.04    99.6 1082.35
   129.5 1067.05   139.4 1058.63     249 1013.06   298.7 1006.01   368.5  988.15
   428.5  983.62   438.5  983.32   448.5  984.94   458.6  989.19   528.8 1005.33
   538.9 1009.38     549 1015.49   599.6 1030.76   609.7 1035.82   619.8 1045.75
   629.9 1052.15   690.6 1081.76   700.7 1091.85   741.1 1115.81   761.3 1132.68
   771.5 1150.03     822  1189.1   842.2 1201.98   852.3 1212.24   902.9 1237.25
#Mann= 3 , 0 , 0
       0      .1       0   428.5    .045       0   448.5      .1       0
Bank Sta=428.5,448.5
XS Rating Curve= 0 ,0
Exp/Cntr=0.3,0.1

Type RM Length L Ch R = 1 ,9215.8  ,80.6,79.4,79
XS GIS Cut Line= 4
     1680921.086       207053.45     1680630.664      207064.981
     1680251.815      207075.805     1679965.344      207117.594
#Sta/Elev= 30
      10  1145.1    70.2 1136.64   140.3 1117.28   150.3 1113.57   160.4 1107.97
   190.4 1098.21   220.5 1086.77   230.5 1078.55   260.6 1062.88   280.6 1053.33
   300.6 1046.16   310.6 1040.13   370.4 1019.44   390.4 1009.49   450.2  989.49
   470.2  977.31   474.1  976.88   480.2  976.21   486.2  976.58     530  981.89
   579.9  984.26   599.8  986.84   609.8  989.62   669.7  1013.9   689.6 1024.56
   759.5 1049.95   769.5  1058.6   849.3 1093.88   919.2 1113.89   959.2 1122.39
#Mann= 3 , 0 , 0
       0      .1       0   474.1    .045       0   486.2      .1       0
Bank Sta=474.1,486.2
XS Rating Curve= 0 ,0
Exp/Cntr=0.3,0.1

Type RM Length L Ch R = 1 ,9136.3  ,172.3,172.5,181
XS GIS Cut Line= 3
     1680900.391       206950.19      1680442.69      206990.955
     1679988.133       207013.82
#Sta/Elev= 30
      10 1212.79    59.9 1191.02    69.9 1182.81   129.9 1156.07   139.9 1147.42
   209.8 1114.67   219.8  1105.8   229.8 1099.61   279.7 1072.64   289.7 1063.51
   299.7 1056.81   359.6 1030.56   379.6 1016.67   429.5  992.27   449.5  975.74
   453.4  975.15   459.5  974.24   465.6  974.54   550.5  983.56   661.8 1004.66
   671.9 1007.61     682 1012.09   732.6 1025.86   783.2 1046.94   813.5 1054.06
   833.7 1061.06   884.3  1074.5   894.4 1077.74   904.5  1082.6   914.6  1085.3
#Mann= 3 , 0 , 0
       0      .1       0   453.4    .045       0   465.6      .1       0
Bank Sta=453.4,465.6
XS Rating Curve= 0 ,0
Exp/Cntr=0.3,0.1

Type RM Length L Ch R = 1 ,8963.8  ,127.2,126.9,126.6
XS GIS Cut Line= 2
     1680725.075      206794.809     1680013.079      206858.952
#Sta/Elev= 30
    10.1 1183.04    20.1 1177.48    40.3 1163.18    60.4 1141.15    90.6 1120.53
   120.8 1102.12   130.9  1094.4     141 1085.18   191.3 1056.36   201.4 1048.66
   211.4 1038.14   271.9 1000.05   281.9  991.85     292  978.22   302.1  972.24
     306  971.66   312.1  970.75   318.3  971.19   422.9  979.25     433  981.38
     443  986.12   483.3  995.08   503.4 1000.49   513.5 1006.42   543.7 1016.82
     584 1032.12   594.1  1039.7   654.5 1065.19   664.5 1073.05   714.9 1097.09
#Mann= 3 , 0 , 0
       0      .1       0     306    .045       0   318.3      .1       0
Bank Sta=306,318.3
XS Rating Curve= 0 ,0
Exp/Cntr=0.3,0.1

Type RM Length L Ch R = 1 ,8837    ,87.6,87.2,86.9
XS GIS Cut Line= 4
     1680747.927      206687.134     1680518.613      206688.738
     1680205.912      206717.602     1680019.895      206767.314
#Sta/Elev= 30
      10 1210.37    19.9 1200.37    49.9 1181.81    69.8 1165.93    79.8 1157.45
    89.7 1142.94   139.6 1106.18   159.5 1094.34   169.5 1083.62   229.3 1050.99
   249.6 1033.74   290.1 1004.73   310.4  988.42   320.5  972.09   324.5  970.42
   330.6  967.87   336.8  968.17   431.9  972.48   452.2  974.24   462.3  976.53
   482.6  988.27   533.2 1008.44   543.4 1015.33   553.5 1020.25   614.3 1043.73
   634.6 1055.87   685.2 1076.64   695.4  1082.1   705.5 1090.41   735.9    1104
#Mann= 3 , 0 , 0
       0      .1       0   324.5    .045       0   336.8      .1       0
Bank Sta=324.5,336.8
XS Rating Curve= 0 ,0
Exp/Cntr=0.3,0.1