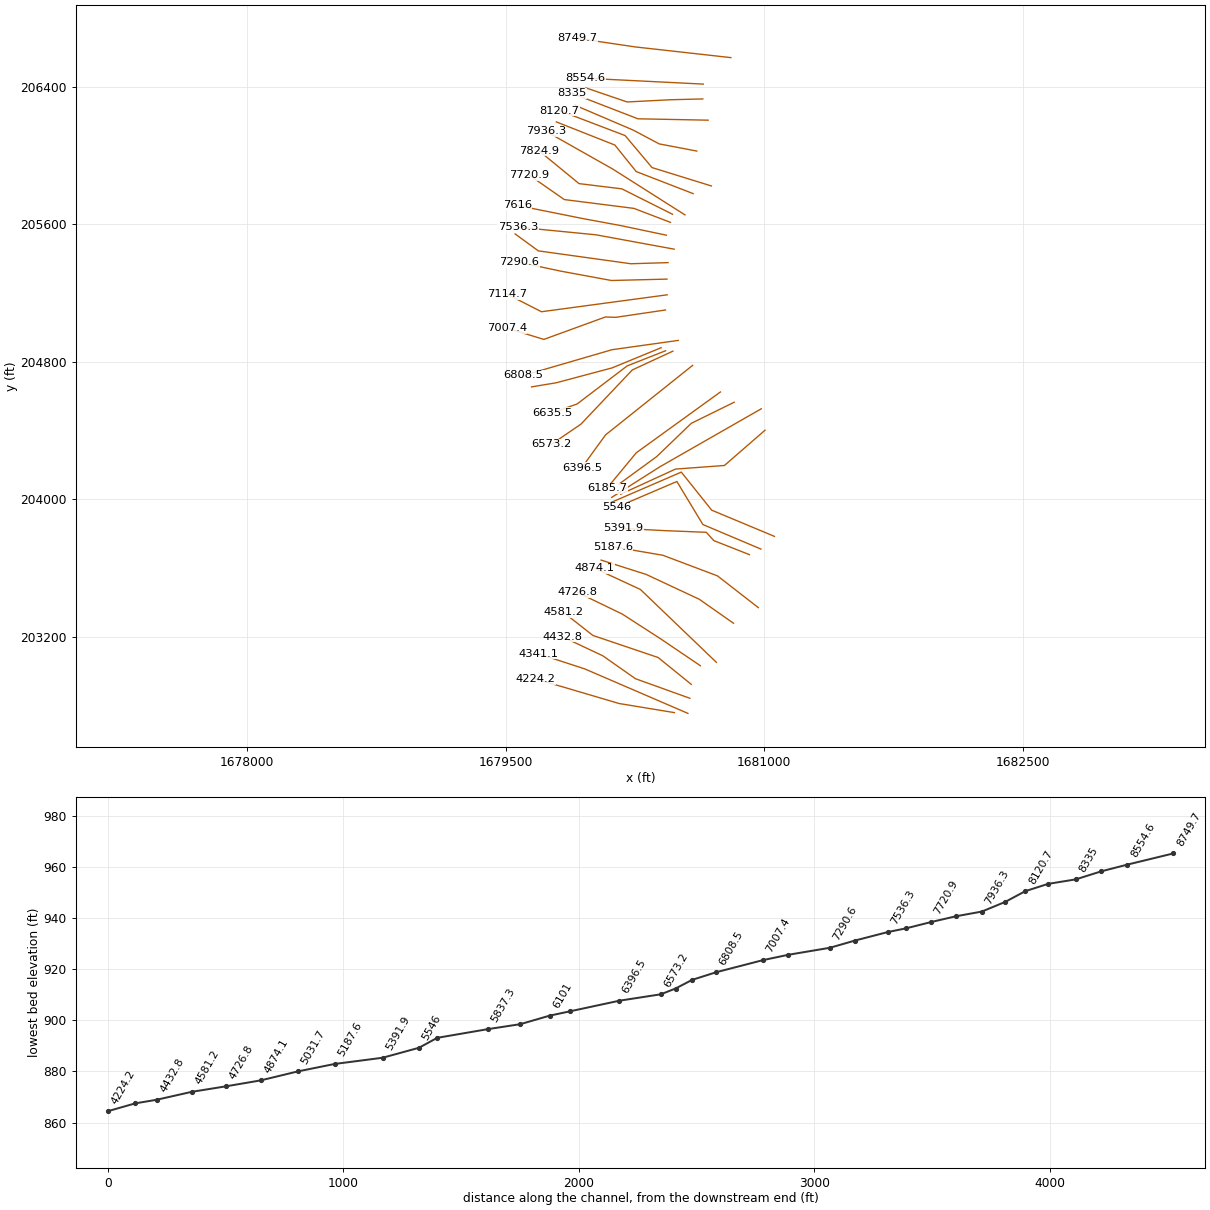
HEC-RAS study lmcrk.prj: lmcrk

--- lmcrk.g01 (geometry) --- (continued)

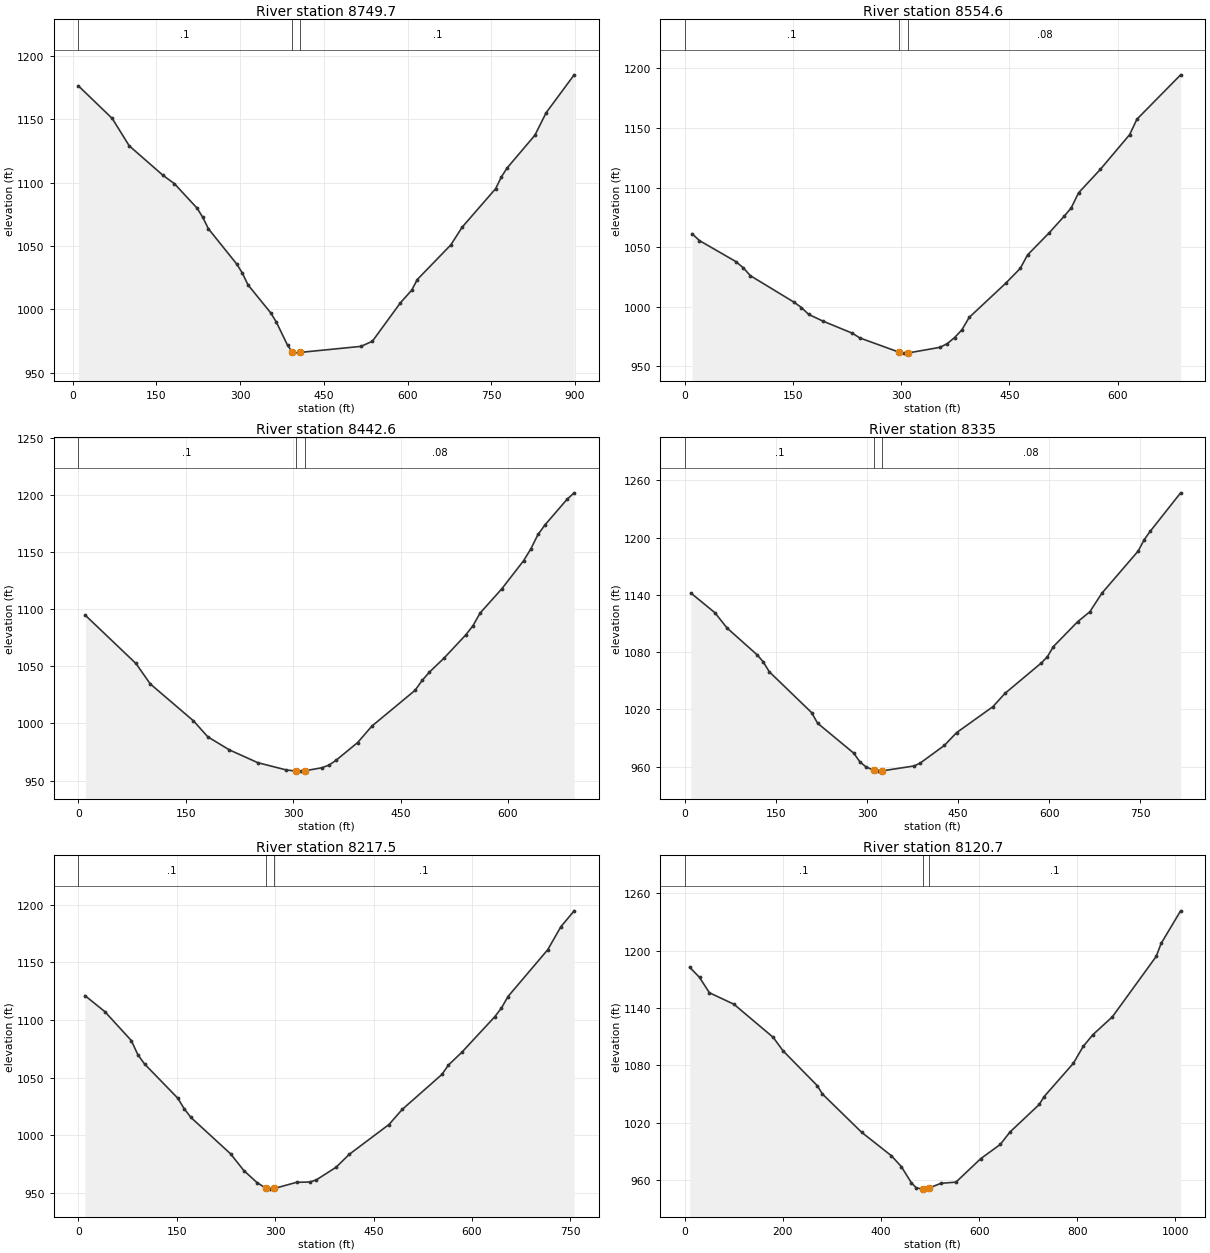
Type RM Length L Ch R = 1 ,8749.7  ,193.9,195.1,196.4
XS GIS Cut Line= 3
     1680806.324      206568.167     1680252.549      206630.173
     1679914.888      206680.269
#Sta/Elev= 30
    10.1 1176.54    70.9 1150.69   101.3 1129.09   162.1 1105.69   182.4 1099.14
   222.9 1079.86     233 1072.71   243.2 1063.57   293.8 1035.78   303.9 1028.66
   314.1 1019.29   354.6  997.27   364.7  990.04     385  971.58  392.95   966.5
   395.1  965.32  408.12  965.91   516.7  970.67     537   974.7   587.4 1005.16
   607.4 1014.99   617.5 1023.46   677.7 1050.89   697.8 1064.78     758 1095.32
   768.1 1104.45   778.1 1111.43   828.3 1137.51   848.4 1155.25   898.6 1185.19
#Mann= 3 , 0 , 0
    10.1      .1       0  392.95    .045       0  408.12      .1       0
Bank Sta=392.95,408.12
XS Rating Curve= 0 ,0
Exp/Cntr=0.3,0.1

Type RM Length L Ch R = 1 ,8554.6  ,110,112,114.1
XS GIS Cut Line= 2
     1680645.965      206414.222     1679959.626      206448.432
#Sta/Elev= 30
    10.1 1061.26    20.2 1055.51    70.7 1037.87    80.8 1032.73      91 1025.96
   151.6 1003.65   161.7  999.23   171.8  993.42     192   987.7   232.4  977.63
   242.5  973.73     297  961.74   303.2  960.95   309.4  961.07   353.7  965.83
   363.8  968.95   373.9  974.02     384  980.48   394.1  990.91   444.7 1019.59
   464.9 1032.08     475 1043.39   505.3 1062.18   525.5 1075.73   535.6 1082.96
   545.7 1095.54     576 1115.32   616.5 1144.43   626.6 1157.38   687.2 1194.68
#Mann= 3 , 0 , 0
       0      .1       0     297    .045       0   309.4     .08       0
Bank Sta=297,309.4
XS Rating Curve= 0 ,0
Exp/Cntr=0.3,0.1

Type RM Length L Ch R = 1 ,8442.6  ,109,107.5,106.1
XS GIS Cut Line= 4
     1680643.693      206327.929     1680452.865      206323.118
     1680204.308      206310.289     1679965.372      206392.072
#Sta/Elev= 30
      10 1094.57    80.4 1052.52   100.5 1034.58   160.7 1002.34   180.8  988.32
   210.8  976.91   250.6  965.68   290.4  959.32   304.1  958.33   310.4  958.29
   316.6   958.6   340.2  961.27   350.2  963.63   360.1   967.9     390  983.32
   409.9  997.71   470.1 1028.98   480.2 1037.78   490.3 1045.01   510.5 1057.12
   540.8  1077.4   550.9 1085.47     561 1096.65   591.3 1117.88   621.6 1142.38
   631.7 1152.66   641.8 1165.41   651.9 1174.03   682.2 1196.07   692.3 1201.86
#Mann= 3 , 0 , 0
       0      .1       0   304.1    .045       0   316.6     .08       0
Bank Sta=304.1,316.6
XS Rating Curve= 0 ,0
Exp/Cntr=0.3,0.1

Type RM Length L Ch R = 1 ,8335    ,126.9,117.5,108.1
XS GIS Cut Line= 3
     1680674.161      206204.452     1680266.848       206212.47
     1679885.795      206360.218
#Sta/Elev= 30
     9.9 1141.87    49.7 1121.13    69.6 1105.13   119.2 1077.01   129.2  1069.6
   139.1 1059.29   208.7 1016.53   218.6 1005.38   278.2  973.95   288.2   964.9
   298.1  959.68   311.7  955.85     318  955.16   324.2  955.38   377.6   960.6
   387.5  963.61   427.3  982.14   447.3  995.47   507.1  1022.7     527 1036.65
   586.8 1068.52   596.8 1075.05   606.8 1085.77   646.6 1111.75   666.6 1122.15
   686.5 1141.62   746.3 1185.88   756.3 1197.91   766.2 1206.65   816.1 1246.84
#Mann= 3 , 0 , 0
       0      .1       0   311.7    .045       0   324.2     .08       0
Bank Sta=311.7,324.2
XS Rating Curve= 0 ,0
Exp/Cntr=0.3,0.1

Type RM Length L Ch R = 1 ,8217.5  ,104.6,96.9,89.2
XS GIS Cut Line= 4
     1680608.414      206024.849     1680390.325      206066.543
     1680239.587      206146.722     1679906.039      206289.442
#Sta/Elev= 30
    10.1 1121.28    40.4 1107.38    80.7 1082.31    90.8 1069.92   100.9 1061.99
   151.4 1032.38   161.5 1023.01   171.6 1015.57   232.1  983.98   252.2  969.52
   272.3  959.09   286.1  954.12   292.3   953.4   298.6  953.97   332.5   959.3
   352.6  959.58   362.6  961.38   392.8  972.39   412.9   983.6   473.4 1009.46
   493.6 1022.56     554 1052.84   564.1 1061.11   584.3 1072.03   634.6 1102.93
   644.7 1110.44   654.8 1120.49   715.3 1161.06   735.4 1181.08   755.6 1194.81
#Mann= 3 , 0 , 0
       0      .1       0   286.1    .045       0   298.6      .1       0
Bank Sta=286.1,298.6
XS Rating Curve= 0 ,0
Exp/Cntr=0.3,0.1

Type RM Length L Ch R = 1 ,8120.7  ,85.3,84.9,84.5
XS GIS Cut Line= 4
     1680693.003      205821.961     1680348.765      205928.867
     1680192.682      206114.884     1679812.095      206260.277
#Sta/Elev= 30
      10 1182.84      30 1172.14    50.1 1156.12   100.1 1144.09   180.2 1109.42
   200.3  1095.3   270.3 1058.72   280.4 1050.18   360.5 1010.04   421.2  985.47
   441.4  974.14   461.6   957.4   471.8  951.84   485.7  950.59     492  950.55
   498.2  951.81   522.3  956.65   552.7  957.86   603.3  982.48     643   997.3
   662.9 1010.34   722.5 1039.17   732.5 1047.44   792.1 1082.29     812 1099.84
   831.8 1112.17   871.6  1130.9     961 1194.18   970.9 1207.66  1010.7 1241.84
#Mann= 3 , 0 , 0
       0      .1       0   485.7    .045       0   498.2      .1       0
Bank Sta=485.7,498.2
XS Rating Curve= 0 ,0
Exp/Cntr=0.3,0.1

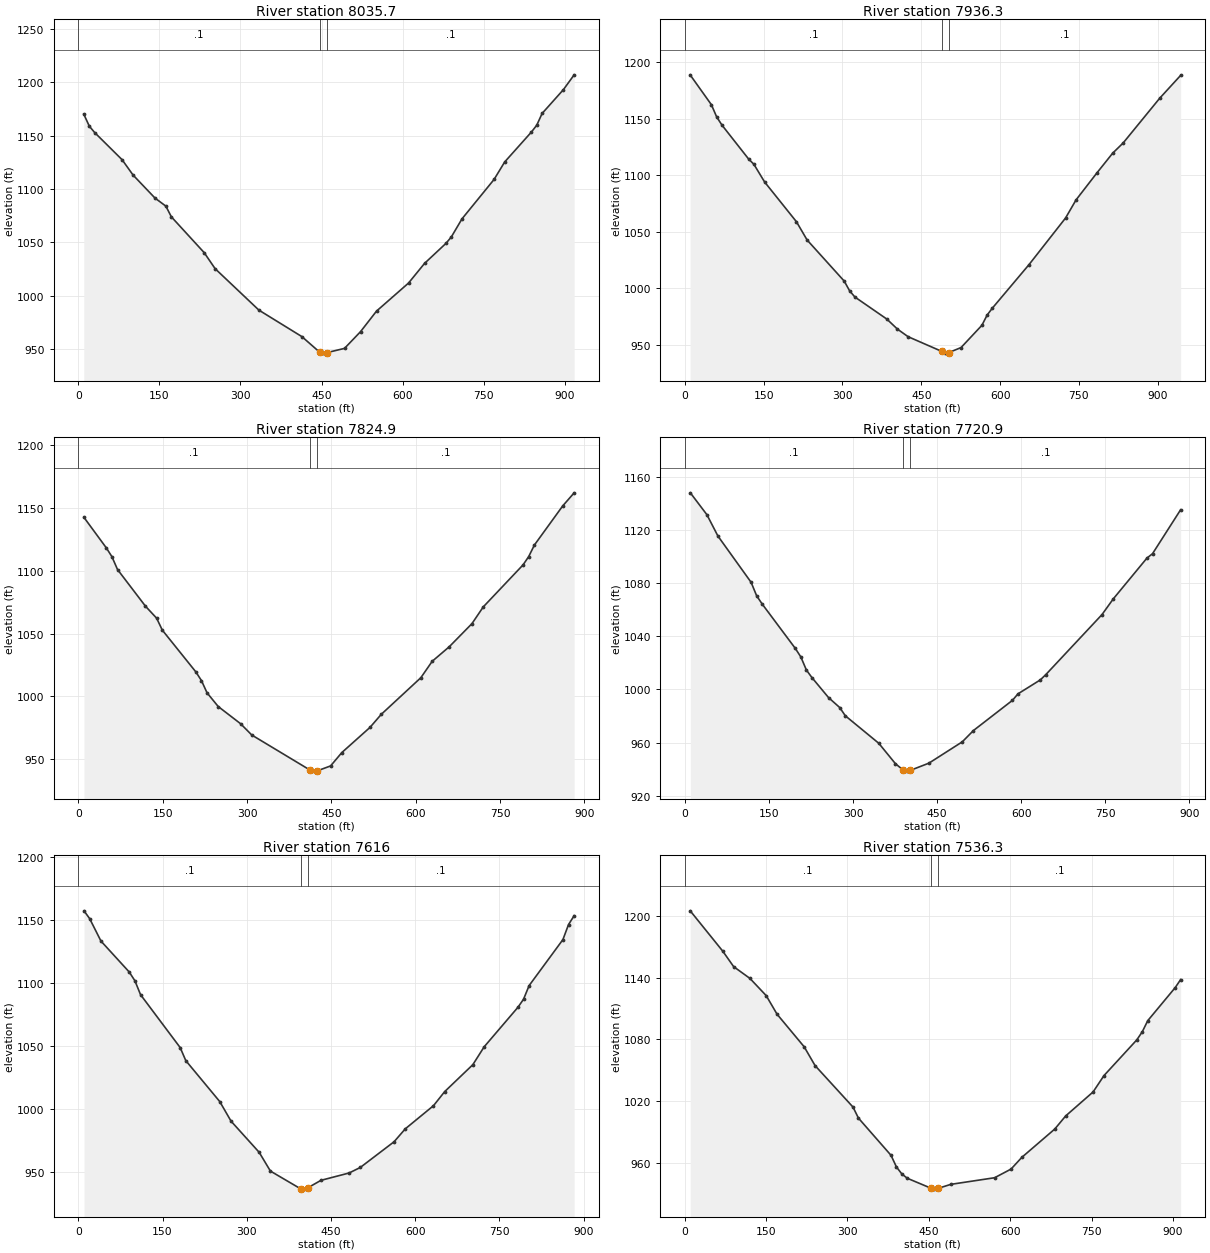
Type RM Length L Ch R = 1 ,8035.7  ,92.7,99.4,107
XS GIS Cut Line= 4
     1680587.166      205777.495     1680256.826      205905.782
     1680133.349      206059.727     1679793.387      206194.429
#Sta/Elev= 30
    10.1 1170.19    20.3 1158.95    30.4 1152.87      81 1127.51   101.3 1113.14
   141.8 1091.62     162 1084.02   172.1 1074.04   232.9 1040.45   253.1 1025.46
   334.1  986.64   413.6  961.84   446.8  947.13     453  946.36   459.3  946.76
   492.5   950.8   522.1  966.44   551.7  985.71     611 1012.02   640.7 1030.47
   680.2 1049.16   690.1 1055.15   709.9 1072.16   769.2 1109.04   788.9 1125.44
   838.3 1153.43   848.2 1159.86   858.1 1170.84   897.6 1193.22   917.4 1207.03
#Mann= 3 , 0 , 0
       0      .1       0   446.8    .045       0   459.3      .1       0
Bank Sta=446.8,459.3
XS Rating Curve= 0 ,0
Exp/Cntr=0.3,0.1

Type RM Length L Ch R = 1 ,7936.3  ,102.5,111.4,119.3
XS GIS Cut Line= 3
     1680540.019      205653.709     1680121.711      205919.732
     1679732.047      206140.409
#Sta/Elev= 30
    10.1 1188.95    50.6  1162.5    60.7 1151.62    70.8 1144.39   121.4 1114.44
   131.5 1109.75   151.8 1094.13   212.5 1058.86   232.7 1042.75   303.5 1006.26
   313.6  997.73   323.7  992.23   384.4  972.73   404.7  963.81   424.9  957.12
   489.4  944.03   495.7  942.57     502  943.02   525.6  947.47   565.4  967.23
   575.3  976.27   585.3  982.43     655 1020.92   724.6 1062.23   744.5 1078.22
   784.3 1102.17   814.2 1119.59   834.1  1128.6   903.7 1168.23   943.5 1188.44
#Mann= 3 , 0 , 0
       0      .1       0   489.4    .045       0     502      .1       0
Bank Sta=489.4,502
XS Rating Curve= 0 ,0
Exp/Cntr=0.3,0.1

Type RM Length L Ch R = 1 ,7824.9  ,104.1,104,104
XS GIS Cut Line= 4
     1680467.297      205657.626      1680173.84      205805.157
     1679925.283      205835.625     1679691.158      206028.056
#Sta/Elev= 30
      10 1142.23    49.8 1117.99    59.7 1111.04    69.7 1100.82   119.4  1071.7
   139.3 1062.15   149.3 1052.73     209 1019.52     219  1012.6   228.9 1002.91
   248.8  992.01   288.6  978.35   308.5  969.39   412.3  941.49   418.6   940.7
   424.9  940.91   448.7  944.84   468.7  955.45   518.8  975.44   538.8  985.79
   609.2 1014.89   629.4 1027.92   659.7 1039.46   700.1 1057.83   720.3 1071.16
     791  1104.5   801.1 1111.14   811.2 1120.28   861.7 1151.42   881.9 1161.73
#Mann= 3 , 0 , 0
       0      .1       0   412.3    .045       0   424.9      .1       0
Bank Sta=412.3,424.9
XS Rating Curve= 0 ,0
Exp/Cntr=0.3,0.1

Type RM Length L Ch R = 1 ,7720.9  ,105.9,104.8,103.8
XS GIS Cut Line= 4
     1680455.671      205610.287     1680243.997      205691.535
     1679839.891       205742.85     1679634.631      205886.105
#Sta/Elev= 30
     9.9  1147.8    39.4 1131.36    59.1 1115.28   118.3 1080.48   128.2 1070.31
     138 1064.18   197.2 1030.73     207 1024.35   216.9 1014.51   226.7 1008.86
   256.5  993.74   276.4  986.28   286.3  980.11     346  959.42   375.8  944.02
   389.3  939.38   395.6  938.47     402     939   435.4  944.46     495  960.52
   514.9  969.02   584.4  991.71   594.3   996.6   634.1 1007.08   644.1 1011.14
   744.2 1056.24   764.2 1067.99   824.3  1098.7   834.3 1102.03   884.4 1135.08
#Mann= 3 , 0 , 0
       0      .1       0   389.3    .045       0     402      .1       0
Bank Sta=389.3,402
XS Rating Curve= 0 ,0
Exp/Cntr=0.3,0.1

Type RM Length L Ch R = 1 ,7616    ,79.7,79.7,81.3
XS GIS Cut Line= 4
     1680432.019      205535.753     1680165.822      205591.879
     1679949.336      205631.968     1679566.077      205708.941
#Sta/Elev= 30
    10.1 1157.06    20.2 1150.85    40.3 1133.04    90.7 1108.45   100.8 1101.48
   110.8 1090.48   181.4 1048.45   191.4  1038.1   251.9 1005.57     272  990.02
   322.1  965.27   342.1  950.38   395.8  936.33   402.1  936.04   408.5  937.04
   432.2  943.03   482.2  948.84   502.2  953.25   562.4  973.68   582.4  983.95
   632.5 1002.28   652.6 1013.53   702.7  1034.9   722.8 1049.06   782.9 1080.42
   792.9  1086.8   802.9  1097.7   863.1 1134.23   873.1 1146.18   883.1 1153.21
#Mann= 3 , 0 , 0
       0      .1       0   395.8    .045       0   408.5      .1       0
Bank Sta=395.8,408.5
XS Rating Curve= 0 ,0
Exp/Cntr=0.3,0.1

Type RM Length L Ch R = 1 ,7536.3  ,138.3,139.2,138.4
XS GIS Cut Line= 3
     1680476.977      205454.553     1680024.232      205537.848
     1679572.501      205582.339
#Sta/Elev= 30
      10 1204.74    70.1 1165.51    90.1 1150.54   120.1 1139.13   150.1 1122.42
   170.1 1104.39   220.2 1072.68   240.2 1054.49   310.2 1014.19   320.2  1003.5
   380.3  967.35   390.3  956.03   400.3  949.24   410.3  945.09     454  935.42
   460.3  934.54   466.7  935.21   490.6  939.18   571.3   945.6   601.6  954.01
   621.7  965.49   682.3  992.92   702.4 1005.63   752.9  1028.9     773  1044.8
   833.6 1079.51   843.7 1087.41   853.7 1098.11   904.2 1130.12   914.3    1138
#Mann= 3 , 0 , 0
       0      .1       0     454    .045       0   466.7      .1       0
Bank Sta=454,466.7
XS Rating Curve= 0 ,0
Exp/Cntr=0.3,0.1

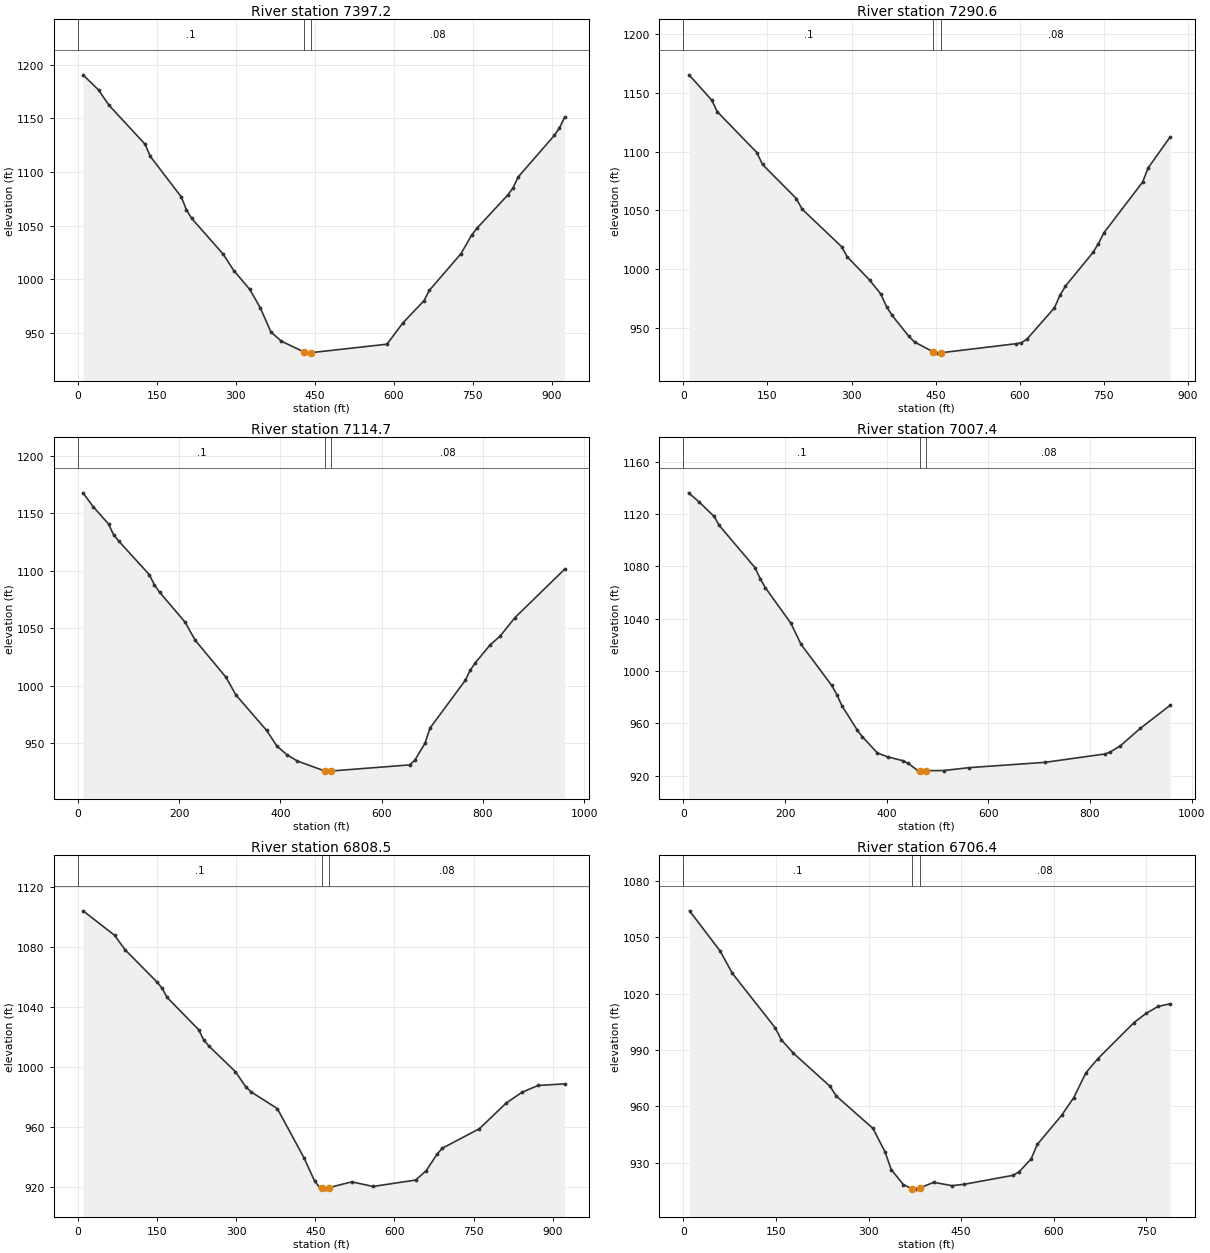
Type RM Length L Ch R = 1 ,7397.2  ,107.5,106.6,105.7
XS GIS Cut Line= 4
     1680441.774      205376.162     1680225.823      205369.747
     1679689.153      205444.582     1679554.451      205542.936
#Sta/Elev= 30
     9.8 1190.53    39.3 1176.44    58.9 1162.31   127.7 1125.87   137.5 1114.61
   196.4 1076.83   206.2 1064.82     216 1056.88   276.3  1023.3   296.3 1008.07
   326.4  990.69   346.5  973.53   366.6  951.02   386.6  942.34   430.4  932.13
   436.8  931.22   443.2  931.65   587.3  939.56   617.4  959.38   657.6  980.08
   667.6  989.65   727.8 1023.87   747.9 1041.04   757.9 1047.44   816.8 1078.61
   826.6 1085.15   836.4 1095.31   905.1 1134.08   914.9 1141.05   924.7 1151.01
#Mann= 3 , 0 , 0
       0      .1       0   430.4    .045       0   443.2     .08       0
Bank Sta=430.4,443.2
XS Rating Curve= 0 ,0
Exp/Cntr=0.3,0.1

Type RM Length L Ch R = 1 ,7290.6  ,169.4,175.9,182.3
XS GIS Cut Line= 4
     1680435.627       205280.38     1680113.304      205272.362
     1679818.243      205326.885     1679577.703        205378.2
#Sta/Elev= 30
    10.1 1165.42    50.4 1143.91    60.5 1133.95     131 1099.24   141.1 1089.06
   201.5 1060.01   211.6 1051.11   282.1 1019.12   292.2 1010.47   332.4  990.54
   352.4  978.55   362.4  967.94   372.4  960.45   402.4  942.64   412.4  937.85
   446.1  929.37   452.4  928.39   458.8  928.67   592.5  936.36   602.5  937.22
   612.5  940.12   661.8  966.89   671.7  977.59   681.5  985.48   730.7  1014.1
   740.5 1021.76   750.4 1031.03   819.2 1074.04   829.1 1086.17   868.4 1112.51
#Mann= 3 , 0 , 0
       0      .1       0   446.1    .045       0   458.8     .08       0
Bank Sta=446.1,458.8
XS Rating Curve= 0 ,0
Exp/Cntr=0.3,0.1

Type RM Length L Ch R = 1 ,7114.7  ,103.6,107.3,111.2
XS GIS Cut Line= 3
     1680436.428      205189.076     1679707.327      205090.722
     1679506.595      205193.353
#Sta/Elev= 30
    10.1 1167.83    30.2  1155.8    60.5 1140.73    70.5 1131.42    80.6 1125.88
   141.1 1096.61   151.2 1087.71   161.3  1081.4   211.6 1055.34   231.8 1039.47
   292.3 1007.46   312.4  991.76   372.9  961.02     393  947.43   413.2  939.85
   433.4  934.47   487.4  925.79   493.8  925.66   500.2  925.76   655.1  931.09
   665.2  935.07   685.3  949.74   695.4  963.16   765.1 1004.71   774.9 1013.55
   784.7 1019.83   814.1  1035.5   833.7 1043.11   863.1 1059.23   961.2 1101.37
#Mann= 3 , 0 , 0
       0      .1       0   487.4    .045       0   500.2     .08       0
Bank Sta=487.4,500.2
XS Rating Curve= 0 ,0
Exp/Cntr=0.3,0.1

Type RM Length L Ch R = 1 ,7007.4  ,199.8,198.9,197.9
XS GIS Cut Line= 5
     1680426.807      205100.878      1680138.16      205058.115
     1680078.292      205060.253     1679721.225      204929.828
     1679505.274       204996.11
#Sta/Elev= 30
    10.1 1136.08    30.2 1129.37    60.4 1118.04    70.4 1111.21   140.9 1078.93
   150.9 1070.65     161 1063.75   211.3 1036.62   231.4 1020.41   291.8  989.02
   301.8  982.05   311.8  973.57   341.7  955.12   351.7  949.98   381.7  937.45
   401.7   934.5   431.7  931.53   441.7  929.63   461.7  923.88   465.3  923.77
   471.7  923.58   478.2  923.92   511.8  924.03   561.8  926.22   711.8  930.31
   830.1  936.72   839.9  938.26   859.5  942.83   898.8  956.19   957.7  973.86
#Mann= 3 , 0 , 0
       0      .1       0   465.3    .045       0   478.2     .08       0
Bank Sta=465.3,478.2
XS Rating Curve= 0 ,0
Exp/Cntr=0.3,0.1

Type RM Length L Ch R = 1 ,6808.5  ,102.6,102.1,101.6
XS GIS Cut Line= 3
     1680500.957      204923.986     1680116.778       204869.96
     1679603.642      204720.238
#Sta/Elev= 30
     9.9 1104.42    69.6 1088.11    89.5 1078.44   149.2 1057.22   159.2 1053.05
   169.1  1046.7   228.8 1025.18   238.7 1018.22   248.7 1014.11   298.4  997.21
   318.3  987.05   328.3  983.69     378  972.53   428.3   939.9   448.5  924.38
   458.6  919.81   462.2  919.46   468.6  918.84   475.1  919.75   519.1   923.7
   559.4  920.62   640.1  924.89   660.3  931.17   680.4  941.99   690.5  946.09
   761.1  959.16   811.6  976.17   841.8  983.46   872.1  987.95   922.5  989.02
#Mann= 3 , 0 , 0
       0      .1       0   462.2    .045       0   475.1     .08       0
Bank Sta=462.2,475.1
XS Rating Curve= 0 ,0
Exp/Cntr=0.3,0.1

Type RM Length L Ch R = 1 ,6706.4  ,63.1,70.9,78.8
XS GIS Cut Line= 4
      1680401.55      204881.486     1680117.714      204764.424
     1679793.788      204677.829     1679649.464      204653.776
#Sta/Elev= 30
     9.9 1064.08    59.4 1042.73    79.2 1030.83   148.6 1001.83   158.5  995.43
   178.3  988.22   237.7  970.57   247.6  965.46     307  948.22   326.8  935.62
   336.6  926.29   356.3  918.29   369.6  916.14   376.1  915.85   382.5  916.42
   405.6  919.48   435.2  917.69     455  918.43   533.8  923.19   543.7  925.03
   563.4  931.98   573.3  939.65   612.7  955.13   632.5  964.65   652.1  977.86
   671.6  985.36   730.1 1004.58   749.6 1009.46   769.1 1013.17   788.6 1014.57
#Mann= 3 , 0 , 0
       0      .1       0   369.6    .045       0   382.5     .08       0
Bank Sta=369.6,382.5
XS Rating Curve= 0 ,0
Exp/Cntr=0.3,0.1

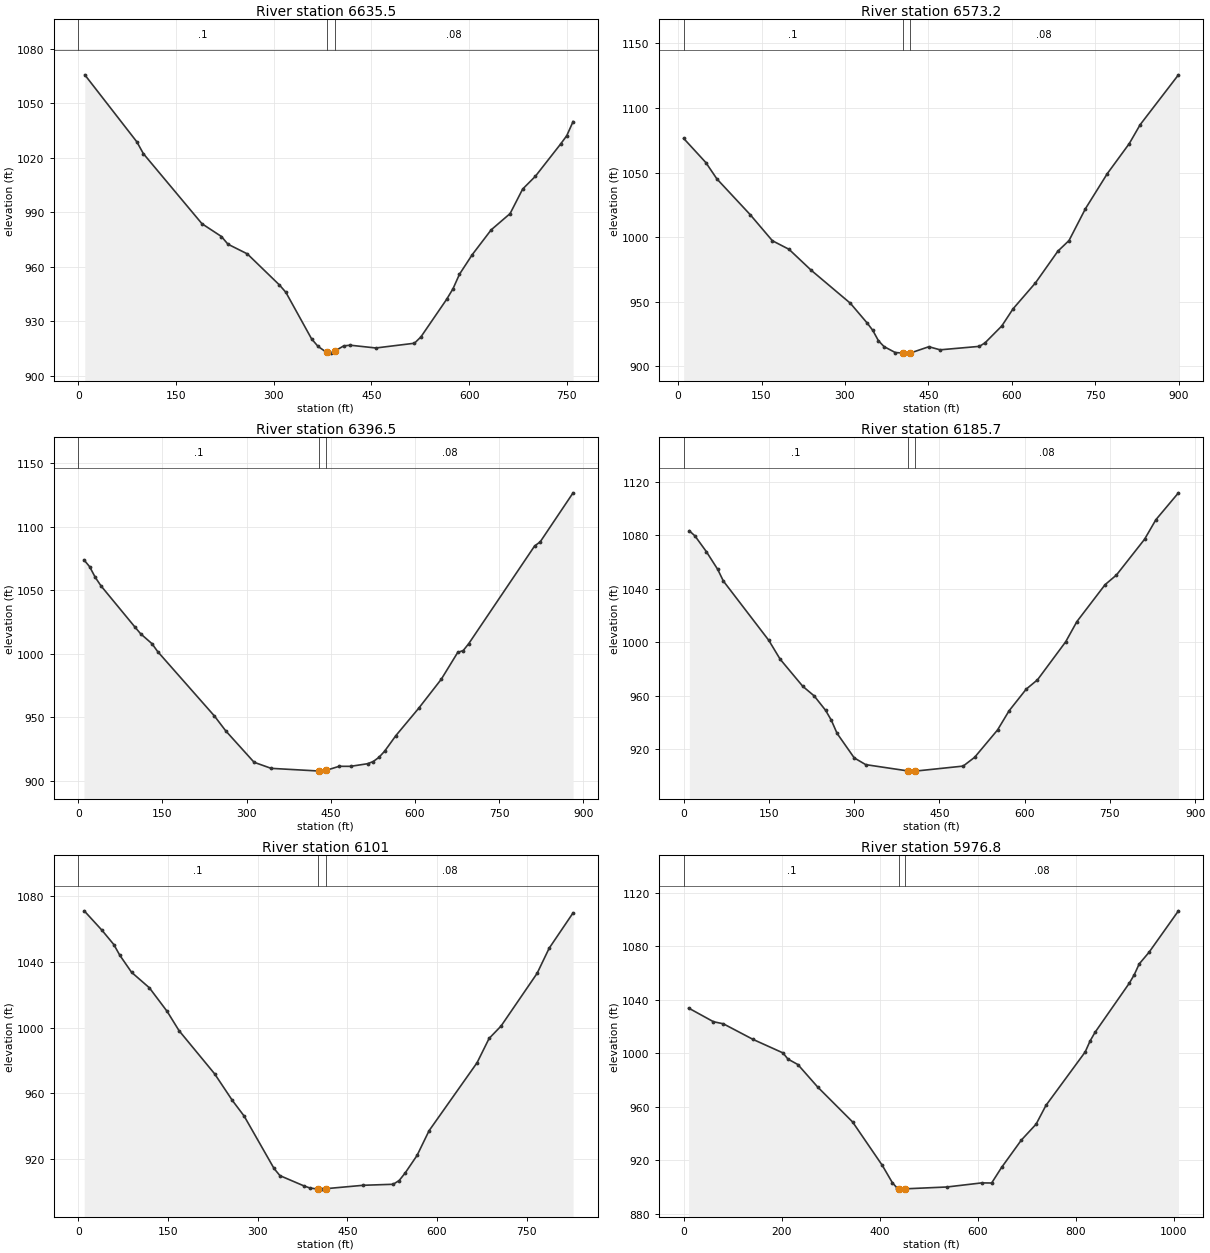
Type RM Length L Ch R = 1 ,6635.5  ,59,62.2,65.5
XS GIS Cut Line= 4
     1680427.208      204863.847     1680204.308      204775.649
     1679914.057      204554.353      1679768.13      204503.038
#Sta/Elev= 30
      10 1065.54    89.9 1028.67    99.9 1022.18   189.8  983.64   219.7  976.61
   229.7  972.38   259.4  967.06   308.8  949.92   318.6   945.9   358.1  920.28
     368  916.14   381.2  912.86   387.7  912.46   394.2  913.72   407.4  916.44
   417.3  916.82   456.7  915.29   515.9   917.9   525.8  921.37   565.2  941.99
   575.1  947.87     585  955.84   604.7  966.66   633.7  980.28   662.7  989.21
     682 1002.71   701.4 1009.69   740.1 1027.41   749.7 1032.08   759.4 1039.86
#Mann= 3 , 0 , 0
       0      .1       0   381.2    .045       0   394.2     .08       0
Bank Sta=381.2,394.2
XS Rating Curve= 0 ,0
Exp/Cntr=0.3,0.1

Type RM Length L Ch R = 1 ,6573.2  ,179.5,176.7,173.9
XS GIS Cut Line= 4
     1680469.569      204861.408     1680234.375      204752.363
     1679936.508       204437.29     1679766.126      204320.462
#Sta/Elev= 30
      10 1076.48    49.9 1057.77    69.8 1045.09   129.6 1017.44   169.5  997.23
   199.4  990.59   239.3  974.37   309.7  948.81   339.9  933.51     350  927.83
   360.1  919.84   370.2  915.27   390.3  910.68     404  910.26  410.59   910.2
     417  910.21   450.8  915.16     471  912.76   541.6  915.44   551.7  918.13
   581.9  931.24   602.1  944.49   642.4  964.58   682.7  989.17   702.7  997.37
   732.2    1022   771.5 1049.16   810.9 1072.37   830.6 1087.08   899.4 1125.68
#Mann= 3 , 0 , 0
      10      .1       0     404    .045       0     417     .08       0
Bank Sta=404,417
XS Rating Curve= 0 ,0
Exp/Cntr=0.3,0.1

Type RM Length L Ch R = 1 ,6396.5  ,214.4,210.9,207.2
XS GIS Cut Line= 3
      1680584.36      204778.856     1680079.228       204374.75
     1679941.399      204184.534
#Sta/Elev= 30
    10.1 1074.02    20.2 1068.66    30.3 1060.22    40.4  1053.6   101.1 1021.05
   111.2 1015.79   131.4    1008   141.5  1001.8   242.6   951.1   262.8  939.38
   313.3  914.65   343.7  909.87   428.1  907.78   434.6  907.68   441.1  908.21
   464.9  911.48   485.2  911.45   515.5  913.51   525.6  915.23   535.7  918.49
   545.8   923.3     566  935.66   606.5   957.1   646.9  980.04   676.2 1001.14
     686 1002.63   695.8 1008.03   813.3    1085   823.1 1088.15   881.8  1126.8
#Mann= 3 , 0 , 0
       0      .1       0   428.1    .045       0   441.1     .08       0
Bank Sta=428.1,441.1
XS Rating Curve= 0 ,0
Exp/Cntr=0.3,0.1

Type RM Length L Ch R = 1 ,6185.7  ,80.4,84.7,88.9
XS GIS Cut Line= 4
     1680745.388      204624.076     1680559.371      204489.374
     1680257.227      204270.517     1680086.845      204063.887
#Sta/Elev= 30
      10 1083.44      20 1079.54    39.9 1067.87    59.9 1054.58    69.9 1045.82
   149.8 1001.42   169.8   987.3   209.7  966.97   229.7  959.81   249.8  949.01
   259.9  941.58     270  931.75   300.2   913.4   320.4  908.36   394.5  903.66
   401.1   903.5   407.6  903.52   491.8  907.27     512  913.85   552.3  934.31
   572.5   948.6   602.7  964.86   622.6  971.86   672.2 1000.32     692  1015.5
   741.6 1043.12   761.5 1050.31     811 1077.09   830.9 1091.71   870.6 1111.84
#Mann= 3 , 0 , 0
       0      .1       0   394.5    .045       0   407.6     .08       0
Bank Sta=394.5,407.6
XS Rating Curve= 0 ,0
Exp/Cntr=0.3,0.1

Type RM Length L Ch R = 1 ,6101    ,128.1,124.2,120
XS GIS Cut Line= 4
     1680825.501      204564.576     1680576.542      204441.901
     1680375.692      204248.267     1680156.801      204088.308
#Sta/Elev= 30
     9.9 1071.07    39.6 1059.27    59.5 1050.54    69.4 1044.08    89.2 1033.66
   118.9 1024.27   148.7 1009.88   168.5  998.22     228  971.98   257.7  955.77
   277.5  946.22   327.4   914.4   337.3  910.04   377.2  903.84   387.1  902.57
   400.5  901.85   407.1  901.84   413.6   902.1   476.8  904.18   526.6  904.79
   536.6  907.04   546.6  911.59   566.6  922.32   586.7  937.36     667  978.71
   687.1  993.47   707.1    1001   767.4 1033.06   787.5 1048.29   827.6 1069.84
#Mann= 3 , 0 , 0
       0      .1       0   400.5    .045       0   413.6     .08       0
Bank Sta=400.5,413.6
XS Rating Curve= 0 ,0
Exp/Cntr=0.3,0.1

Type RM Length L Ch R = 1 ,5976.8  ,148.4,139.5,130.9
XS GIS Cut Line= 3
     1680982.623      204526.449     1680393.532      204188.733
     1680114.695      204011.324
#Sta/Elev= 30
    10.1 1033.94    60.8 1023.73    81.1 1022.15   141.9 1010.44   202.7 1000.39
   212.8  995.79   233.1  991.68   273.6  974.84   344.6  948.81   405.4  916.22
   425.7  903.42   435.8  899.21   439.3  898.97   445.9  898.51   452.5  898.74
   537.1  900.11   608.1  903.17   628.4  903.09   648.6   914.7     689   935.2
   719.1   947.1   739.1  961.08   819.2 1001.08   829.3 1009.37   839.3 1015.76
   909.4 1052.63   919.4  1058.9   929.4 1066.93   949.4 1075.61  1009.5 1106.66
#Mann= 3 , 0 , 0
       0      .1       0   439.3    .045       0   452.5     .08       0
Bank Sta=439.3,452.5
XS Rating Curve= 0 ,0
Exp/Cntr=0.3,0.1

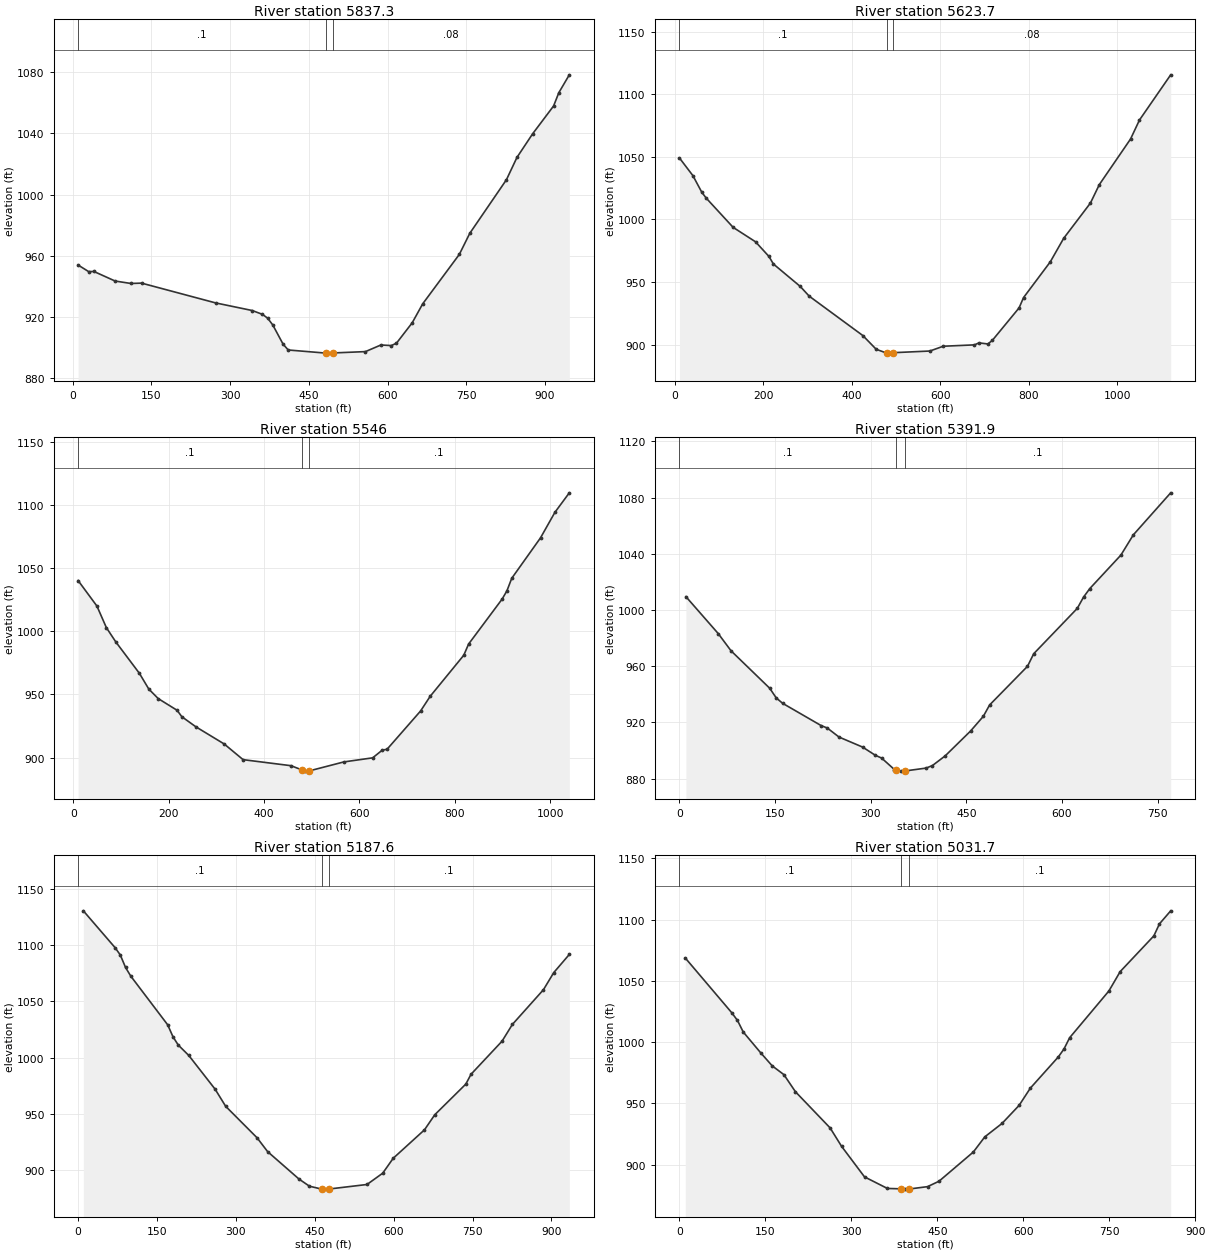
Type RM Length L Ch R = 1 ,5837.3  ,233.1,213.6,194.1
XS GIS Cut Line= 4
     1681004.502      204402.011     1680768.773      204196.751
     1680484.937      204175.904     1680167.425      204029.977
#Sta/Elev= 30
    10.1  954.05    30.2  949.76    40.3  949.84    80.7   943.6   110.9  942.01
   131.1  942.24   272.2  929.33     342  924.36   361.6  921.85   371.5  919.34
   381.3   914.9   400.9   902.4   410.7  898.59   482.6  896.55  489.26  896.54
   495.8  896.65   557.9  897.53   587.4  901.86   607.2  901.47   617.1  903.03
   647.1  916.35   667.1  928.73   736.9  960.99   756.9  974.78   826.8 1009.78
   846.8 1024.31   876.7 1039.73   916.7 1057.92   926.6 1066.55   946.6 1078.22
#Mann= 3 , 0 , 0
    10.1      .1       0   482.6    .045       0   495.8     .08       0
Bank Sta=482.6,495.8
XS Rating Curve= 0 ,0
Exp/Cntr=0.3,0.1

Type RM Length L Ch R = 1 ,5623.7  ,82.6,77.7,74.3
XS GIS Cut Line= 4
     1681058.956      203784.621     1680695.008      203936.969
     1680518.613      204158.265       1680111.3      203981.869
#Sta/Elev= 30
    10.1 1049.02    40.5  1034.9    60.7 1021.58    70.8  1016.9   131.5  993.61
   182.1   982.1   212.4  970.42   222.6  964.35   283.3  946.43   303.5  938.69
   424.9   907.2   455.2  896.21   478.9  893.18   485.5  893.16   492.2  893.48
   576.5  894.84   606.8  898.66   677.5  899.76   687.6  901.34   707.8  900.49
   717.9  903.35   778.4   929.3   788.5  937.54     849  966.08   879.3  984.88
   939.8 1013.04     960 1027.82  1030.6 1064.22  1050.8  1079.4  1121.4 1115.47
#Mann= 3 , 0 , 0
    10.1      .1       0   478.9    .045       0   492.2     .08       0
#XS Ineff= 2 , 0
       0                     525       0
Permanent Ineff=
       F       F
Bank Sta=478.9,492.2
XS Rating Curve= 0 ,0
Exp/Cntr=0.3,0.1

Type RM Length L Ch R = 1 ,5546    ,131.5,154.1,175.1
XS GIS Cut Line= 4
     1680980.448      203710.862     1680643.693      203853.582
     1680492.955      204103.743     1680141.768      203953.005
#Sta/Elev= 30
     9.9 1040.16    49.4 1019.94    69.2 1002.86      89  991.55   138.4  966.72
   158.2  954.21   177.9   946.7   217.5  937.43   227.4  932.35     257  924.32
   316.3  910.75   355.9  898.34   456.4  893.56     480   890.1   486.6  889.26
   493.3  889.31   567.2  896.55   627.6  899.78   647.7  905.86   657.8  906.56
   728.2  936.92   748.3  948.54   818.7  981.03   828.8  989.87   899.2 1025.53
   909.2 1032.05   919.3 1041.96   979.6 1073.96  1009.8 1094.17    1040 1109.61
#Mann= 3 , 0 , 0
     9.9      .1       0     480    .045       0   493.3      .1       0
#XS Ineff= 2 , 0
       0     465             495       0
Permanent Ineff=
       F       F
Bank Sta=480,493.3
XS Rating Curve= 0 ,0
Exp/Cntr=0.3,0.1

Type RM Length L Ch R = 1 ,5391.9  ,210.7,204.3,197.9
XS GIS Cut Line= 5
     1680913.899      203678.389     1680707.035      203760.172
     1680663.738       203808.28     1680424.802      203817.902
     1680181.056       203830.73
#Sta/Elev= 30
    10.1 1009.48    60.7  983.25    80.9  970.94   141.6  944.28   151.7  937.46
   161.8   933.6   222.4  917.71   231.7  916.07   250.2  909.61   287.2  902.47
   307.1  896.66   317.1  894.64     337  886.52   340.3  886.14   346.9  885.37
   353.6  885.49   386.8  887.53   396.8  889.37   416.7  896.22   456.5  913.89
   476.5  924.33   486.4  932.44   545.8  959.93   555.6  968.91   623.9 1001.15
   633.7 1009.16   643.5 1015.22   692.3 1039.05   711.8 1053.45   770.4 1083.34
#Mann= 3 , 0 , 0
       0      .1       0   340.3    .045       0   353.6      .1       0
Bank Sta=340.3,353.6
XS Rating Curve= 0 ,0
Exp/Cntr=0.3,0.1

Type RM Length L Ch R = 1 ,5187.6  ,157.5,155.9,154.4
XS GIS Cut Line= 4
     1680965.518      203370.332     1680728.283      203555.012
      1680411.84      203674.748     1680120.988      203724.615
#Sta/Elev= 30
      10 1130.73    70.2    1098    80.2 1091.46    90.2 1080.32   100.2 1072.56
   170.4 1029.21   180.4 1018.61   190.4 1011.25   210.5 1001.94   260.6  971.88
   280.6   956.7   340.4  928.61   360.4  916.32   420.1  891.89     440  885.52
   463.1  882.98   469.8  882.93   476.5  882.99   549.4  887.06   579.3  897.14
   599.2  910.39   658.7  935.74   678.3  949.17   737.3  976.45   747.2   985.2
   806.2 1014.67   825.9 1029.61   884.9 1060.49   904.6 1075.77   934.1 1091.89
#Mann= 3 , 0 , 0
       0      .1       0   463.1    .045       0   476.5      .1       0
Bank Sta=463.1,476.5
XS Rating Curve= 0 ,0
Exp/Cntr=0.3,0.1

Type RM Length L Ch R = 1 ,5031.7  ,164.1,157.5,151
XS GIS Cut Line= 4
     1680821.692      203279.495     1680622.846      203419.007
     1680314.956      203563.331      1680053.57      203646.718
#Sta/Elev= 30
    10.1 1068.63    91.1 1024.02   101.2 1017.67   111.3 1008.22   141.7  991.28
   161.9  980.57   182.2  973.45   202.4  959.48   262.9  929.97   282.9  914.94
   322.9  890.02   362.9  880.57   386.2  880.27   392.9  880.02   399.7  880.05
   432.9  882.04   452.9  886.45   512.9  910.33   532.9  922.68   562.9  933.61
   592.7  948.34   612.3   962.4   661.3  987.97   671.1   994.4   680.9 1003.54
   749.5 1041.75   769.1  1057.5   827.9 1086.67   837.7 1096.49   857.3 1107.11
#Mann= 3 , 0 , 0
       0      .1       0   386.2    .045       0   399.7      .1       0
Bank Sta=386.2,399.7
XS Rating Curve= 0 ,0
Exp/Cntr=0.3,0.1

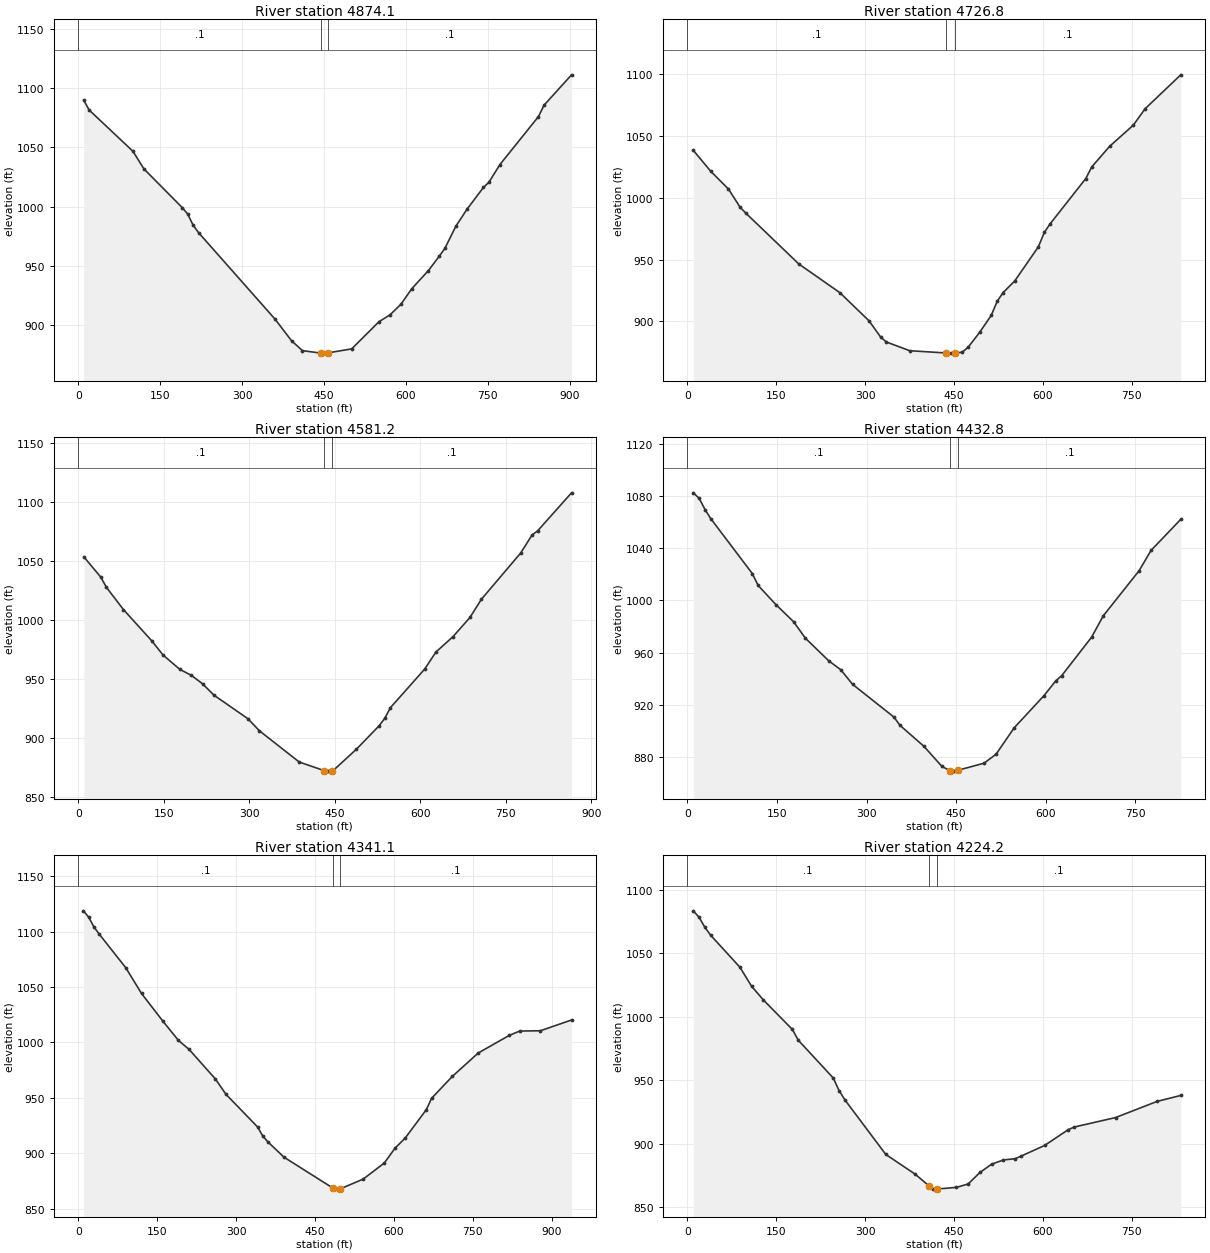
Type RM Length L Ch R = 1 ,4874.1  ,143.4,147.3,151.3
XS GIS Cut Line= 3
     1680721.868      203052.553     1680281.414      203475.902
     1680016.285      203599.091
#Sta/Elev= 30
      10 1089.83      20 1081.43   100.2 1046.65   120.2 1031.86   190.3  999.24
   200.3  993.86   210.3  984.47   220.3  978.09   360.5   905.1   390.6  886.96
   410.6  878.59   443.9  876.57   450.7  876.51   457.4  876.73   500.8  880.11
   550.8  903.02   570.9  908.76   590.9   917.7   610.9  930.87   641.2  946.08
   661.3  958.34   671.4  964.81   691.6  983.56   711.7  997.66     742 1016.18
   752.1 1020.57   772.2 1035.45   842.8 1075.92   852.9 1085.44   903.3 1111.07
#Mann= 3 , 0 , 0
       0      .1       0   443.9    .045       0   457.4      .1       0
Bank Sta=443.9,457.4
XS Rating Curve= 0 ,0
Exp/Cntr=0.3,0.1

Type RM Length L Ch R = 1 ,4726.8  ,140.7,145.6,150.5
XS GIS Cut Line= 4
     1680629.261      203032.541     1680399.947       203188.09
     1680177.047      203332.413     1679915.661      203459.098
#Sta/Elev= 30
     9.9 1038.49    39.6 1021.39    69.3 1007.13    89.1  992.28      99  987.44
     188  946.47   257.3  923.22   306.6  900.42   326.3  887.21   336.1  883.18
   375.4  876.15   437.5  874.29   444.3  874.19   451.1   874.2     464  874.92
   473.8  878.81   493.5  891.02   513.1  904.79     523  916.04   532.8  923.08
   552.7  932.63   592.7  960.35   602.7  971.96   612.7  979.07   672.8 1015.66
   682.9  1025.1   712.9 1041.68     753 1058.88     773 1072.22   833.1 1099.65
#Mann= 3 , 0 , 0
       0      .1       0   437.5    .045       0   451.1      .1       0
Bank Sta=437.5,451.1
XS Rating Curve= 0 ,0
Exp/Cntr=0.3,0.1

Type RM Length L Ch R = 1 ,4581.2  ,154,148.4,142.8
XS GIS Cut Line= 4
     1680576.476      202924.265     1680384.044      203080.348
     1680005.596      203208.636     1679834.546      203343.338
#Sta/Elev= 30
     9.9 1053.49    39.6 1036.32    49.6 1027.61    79.3 1008.86   128.8  982.49
   148.7   970.4   178.4  958.14   198.2   953.2     218  946.04   237.9  936.42
   297.7  916.38   317.7  906.22   387.6  879.73   430.8  872.55   437.6  872.03
   444.4  872.51   447.6  872.74   487.5  890.42   527.5  910.34   537.5   916.7
   547.5  925.79   607.4  958.35   627.4  972.94   657.3  985.94     687 1002.18
   706.8 1017.43     776  1056.8   795.8 1071.95   805.7 1075.56   865.1 1107.72
#Mann= 3 , 0 , 0
       0      .1       0   430.8    .045       0   444.4      .1       0
Bank Sta=430.8,444.4
XS Rating Curve= 0 ,0
Exp/Cntr=0.3,0.1

Type RM Length L Ch R = 1 ,4432.8  ,87.8,91.7,95.7
XS GIS Cut Line= 4
     1680568.324      202843.317     1680252.416      202957.172
     1680063.192      203090.271     1679829.067      203200.919
#Sta/Elev= 30
     9.9 1082.57    19.8 1078.26    29.6 1069.61    39.5 1062.51   108.6 1020.64
   118.5 1011.44   148.1  996.79   177.8  983.63   197.5     971     237  953.48
   256.8  946.78   276.5  935.61   345.9  910.39   355.9  904.14   396.2  887.92
   426.3   872.5   439.6  869.32   446.4  868.94   453.3  869.65   496.7  875.02
   516.9  881.96     547  902.09     597  926.86   616.9  938.24   626.9  942.31
   676.7   971.7   696.6  988.31   756.4 1022.81   776.3 1038.32   826.1 1062.22
#Mann= 3 , 0 , 0
       0      .1       0   439.6    .045       0   453.3      .1       0
Bank Sta=439.6,453.3
XS Rating Curve= 0 ,0
Exp/Cntr=0.3,0.1

Type RM Length L Ch R = 1 ,4341.1  ,114.5,116.9,119.3
XS GIS Cut Line= 3
     1680556.878      202755.527     1679958.557      203014.066
     1679687.052      203102.785
#Sta/Elev= 30
      10 1118.71    20.1 1112.85    30.1    1104    40.1 1097.59    90.2 1067.47
   120.3 1044.12   160.4 1019.42   190.5 1001.72   210.6  993.68   260.7  966.94
   280.8  953.08   340.9  923.59     351  915.21     361   909.9   391.1  896.31
   484.5  868.31   491.3  867.51   498.2  867.82   541.5  876.55   581.6  891.05
   601.7   904.3   621.7  913.82   661.6  939.35   671.5  949.51   710.9  969.28
   760.1  990.38   819.2 1006.31   838.9 1010.19   878.3 1010.47   937.4 1020.18
#Mann= 3 , 0 , 0
       0      .1       0   484.5    .045       0   498.2      .1       0
Bank Sta=484.5,498.2
XS Rating Curve= 0 ,0
Exp/Cntr=0.3,0.1

Type RM Length L Ch R = 1 ,4224.2  ,102.3,108.6,114.9
XS GIS Cut Line= 4
     1680478.523       202759.93     1680157.804      202812.849
     1679843.499      202905.857     1679670.311      202955.569
#Sta/Elev= 30
     9.9 1083.34    19.7 1078.24    29.6 1070.29    39.4 1064.07    88.7 1038.96
   108.4 1023.96   128.1 1013.33   177.3     990   187.2  981.58   246.3  951.82
   256.1  941.95     266  934.59     335  891.71   384.7  876.16   407.6  867.11
   414.4  864.44   421.3  864.52   454.2  865.82     474  868.49   493.9  877.53
   513.8  884.11   533.6  887.38   553.5  888.39   563.4   890.4   603.2  898.82
   642.9  911.15   652.8  913.24   722.9  920.73     793  933.43     833  938.13
#Mann= 3 , 0 , 0
       0      .1       0   407.6    .045       0   421.3      .1       0
Bank Sta=407.6,421.3
XS Rating Curve= 0 ,0
Exp/Cntr=0.3,0.1