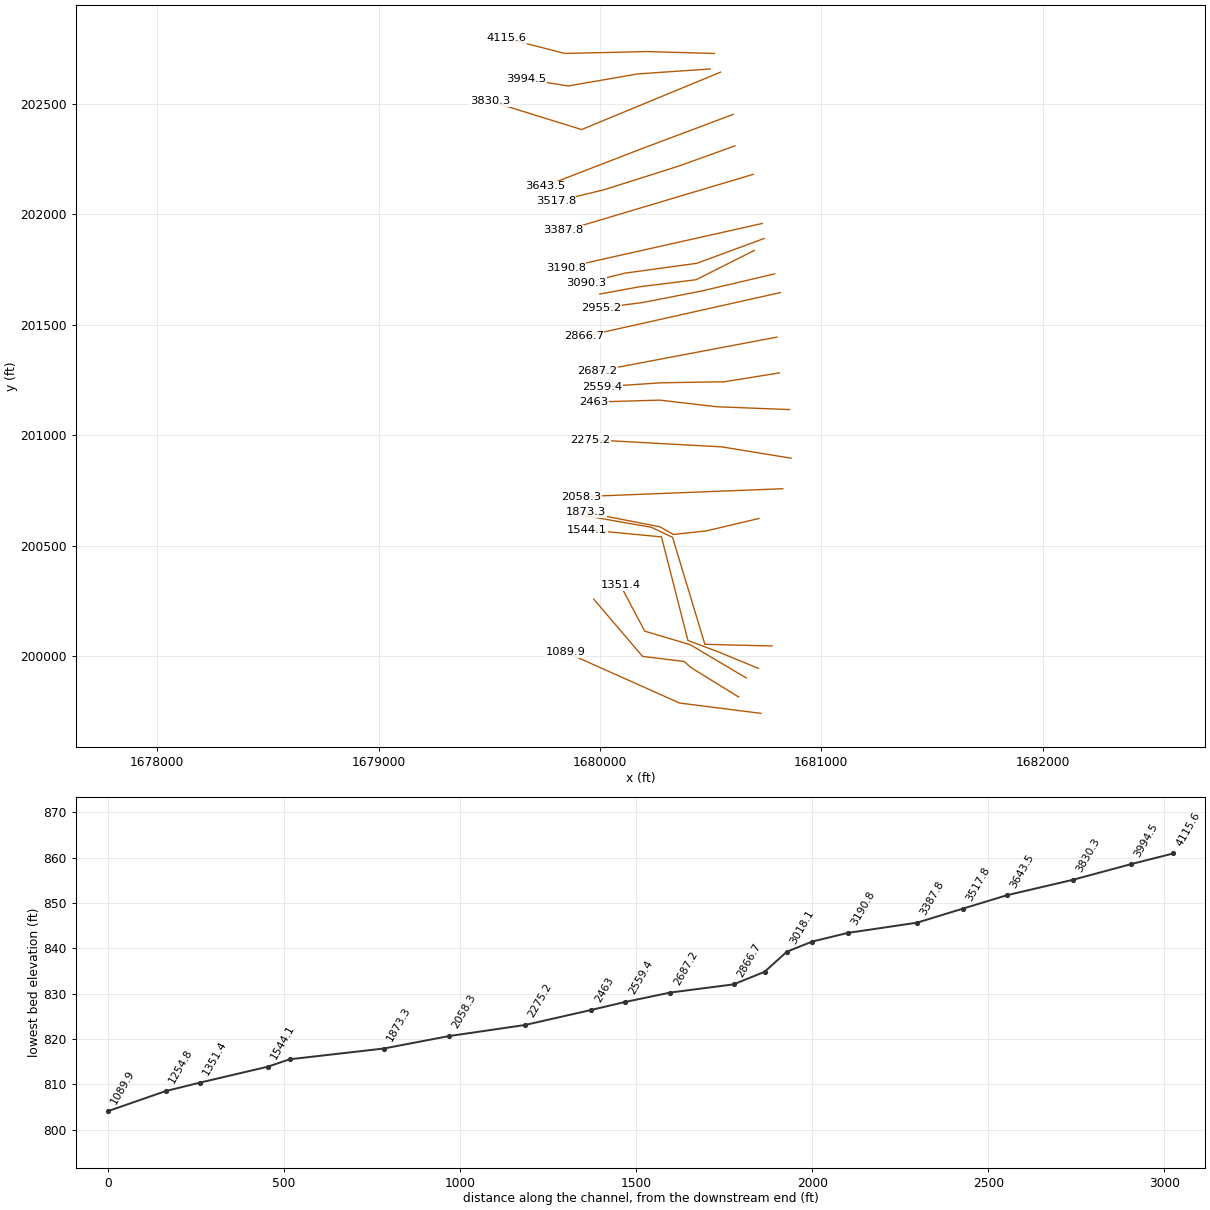
HEC-RAS study lmcrk.prj: lmcrk

--- lmcrk.g01 (geometry) --- (continued)

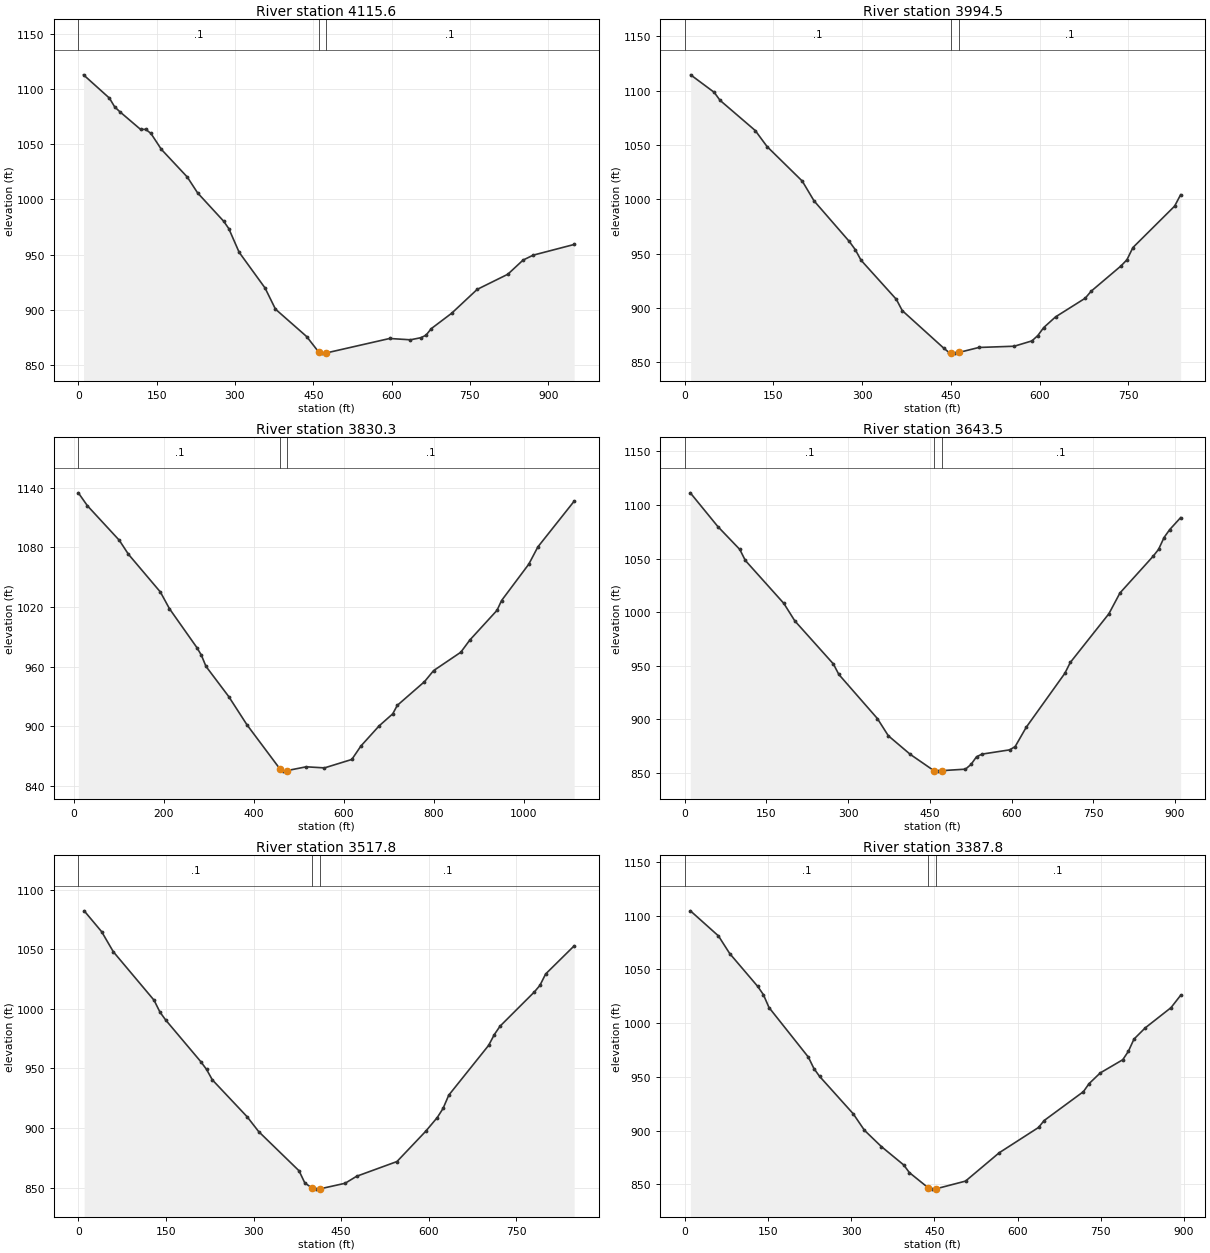
Type RM Length L Ch R = 1 ,4115.6  ,118.2,121.1,124
XS GIS Cut Line= 4
     1680516.608      202727.558     1680208.718       202736.11
      1679840.96      202727.558     1679575.832      202795.978
#Sta/Elev= 30
     9.9 1112.83    59.6 1091.72    69.6 1083.84    79.5 1079.44   119.2 1063.44
   129.2 1063.46   139.1 1059.76     159  1045.4   208.7 1020.32   228.5 1005.95
   278.2  980.42   288.1  973.74     308  952.24   357.7  919.85   377.6  900.76
   437.3  875.97   460.2  862.09   467.1  860.96     474  861.03   596.3  874.21
   636.1  873.02     656  874.91   665.9  877.16   675.9  883.08     715  897.02
   763.9  918.63   822.6  932.34   851.9   945.2   871.4  949.65   949.7   959.3
#Mann= 3 , 0 , 0
       0      .1       0   460.2    .045       0     474      .1       0
Bank Sta=460.2,474
XS Rating Curve= 0 ,0
Exp/Cntr=0.3,0.1

Type RM Length L Ch R = 1 ,3994.5  ,159.8,164.2,168.6
XS GIS Cut Line= 4
     1680497.766        202657.3     1680170.633       202634.85
     1679856.328      202580.328     1679667.104      202610.796
#Sta/Elev= 30
     9.9  1114.6    49.7 1098.51    59.6 1091.15   119.2 1063.33   139.1 1048.63
   198.7 1016.83   218.6  998.65   278.2  961.32   288.2  953.88   298.1  944.05
   357.8  908.05   367.8   897.7   437.6  863.34   447.5   858.9   450.6   858.8
   457.5  858.58   464.4  859.31   497.4  863.79   557.2  864.93   587.1  869.83
   597.1  874.77     607  882.07     627  891.89   677.2  909.09   687.3  915.55
   737.7  938.77   747.8  944.47   757.9   955.7   828.5  993.85   838.6 1004.32
#Mann= 3 , 0 , 0
       0      .1       0   450.6    .045       0   464.4      .1       0
Bank Sta=450.6,464.4
XS Rating Curve= 0 ,0
Exp/Cntr=0.3,0.1

Type RM Length L Ch R = 1 ,3830.3  ,187.4,186.8,186.4
XS GIS Cut Line= 3
      1680544.56      202642.855     1679917.265      202383.085
     1679503.136      202511.607
#Sta/Elev= 30
    10.1  1134.7    30.4 1121.66   101.3 1086.97   121.6 1072.93   192.5 1035.09
   212.8 1018.27   273.6  979.31   283.7   971.6   293.9   960.4   344.5  930.06
   385.1  901.66   459.2  856.87   466.1  855.14   473.1  855.58   516.8  859.48
   557.4  858.39   618.2  866.87   638.4  880.35     679  900.63   709.2  912.69
   719.3  921.19   779.8     945     800  956.09   860.5  974.56   880.6  986.82
   941.1 1016.69   951.2  1026.5  1011.7 1063.03  1031.9 1080.36  1112.6 1126.31
#Mann= 3 , 0 , 0
    10.1      .1       0   459.2    .045       0   473.1      .1       0
#XS Ineff= 2 , 0
       0                   526.9       0
Permanent Ineff=
       F       F
Bank Sta=459.2,473.1
XS Rating Curve= 0 ,0
Exp/Cntr=0.3,0.1

Type RM Length L Ch R = 1 ,3643.5  ,126.8,125.7,124.5
XS GIS Cut Line= 3
      1680601.44      202451.636     1680175.931      202291.485
     1679750.864      202126.727
#Sta/Elev= 30
    10.1 1111.32    60.6 1079.91     101 1058.51   111.1 1048.28   181.9 1008.17
   202.1  991.83   272.8  951.74   282.9  941.91   353.6  900.83   373.8   884.7
   414.2  867.33   457.8  852.06   464.8  851.75   471.7  852.19   515.4  853.58
   525.6     858   535.7  865.13   545.8  867.61   596.5  871.59   606.6   874.6
   626.9  892.59   697.8  942.91   707.9   953.1   778.8  998.56   799.1 1017.92
   859.9 1052.09     870  1058.6   880.1 1069.65   890.3 1076.94   910.5 1088.19
#Mann= 3 , 0 , 0
       0      .1       0   457.8    .045       0   471.7      .1       0
Bank Sta=457.8,471.7
XS Rating Curve= 0 ,0
Exp/Cntr=0.3,0.1

Type RM Length L Ch R = 1 ,3517.8  ,130.3,130,129.6
XS GIS Cut Line= 4
     1680610.017       202309.32     1680356.649      202217.915
     1680018.291      202110.474     1679800.202      202057.556
#Sta/Elev= 30
      10 1082.18    39.9 1064.69    59.9 1047.86   129.7 1007.17   139.7  997.26
   149.6  990.58   209.5  955.76   219.5  949.18   229.4  940.43   289.1   909.4
   308.8     897   377.8  864.17   387.7  853.99   400.4  849.61   407.4  848.78
   414.4  849.09   456.7  853.69   476.4  859.56   545.5  871.92   594.8  897.37
   614.5  908.85   624.4  916.47   634.1  927.57   702.4  969.37   712.2  978.44
   721.9  985.43   780.5 1014.07   790.2 1019.68     800 1029.23   848.8  1052.8
#Mann= 3 , 0 , 0
       0      .1       0   400.4    .045       0   414.4      .1       0
Bank Sta=400.4,414.4
XS Rating Curve= 0 ,0
Exp/Cntr=0.3,0.1

Type RM Length L Ch R = 1 ,3387.8  ,198.4,197,195.6
XS GIS Cut Line= 3
     1680691.934      202180.197     1679877.308      201936.451
     1679834.546      201927.898
#Sta/Elev= 30
    10.1  1104.5    60.7 1081.15      81 1064.75   131.6 1034.13   141.7 1026.54
   151.8 1014.58   222.7  968.49   232.8  957.83   242.9   950.6   303.7  915.71
   323.9  900.38   354.3  885.31   394.8  868.11   404.9  861.04   438.4  847.12
   445.4  845.68   452.4  845.91   506.1  853.14   566.9  879.52   637.7  903.02
   647.9  909.49   718.7  936.35   728.8  943.78   749.1  953.78   789.6  966.03
   799.7  973.84   809.8  985.21   830.1  995.65   876.5 1014.42   893.9 1025.92
#Mann= 3 , 0 , 0
       0      .1       0   438.4    .045       0   452.4      .1       0
Bank Sta=438.4,452.4
XS Rating Curve= 0 ,0
Exp/Cntr=0.3,0.1

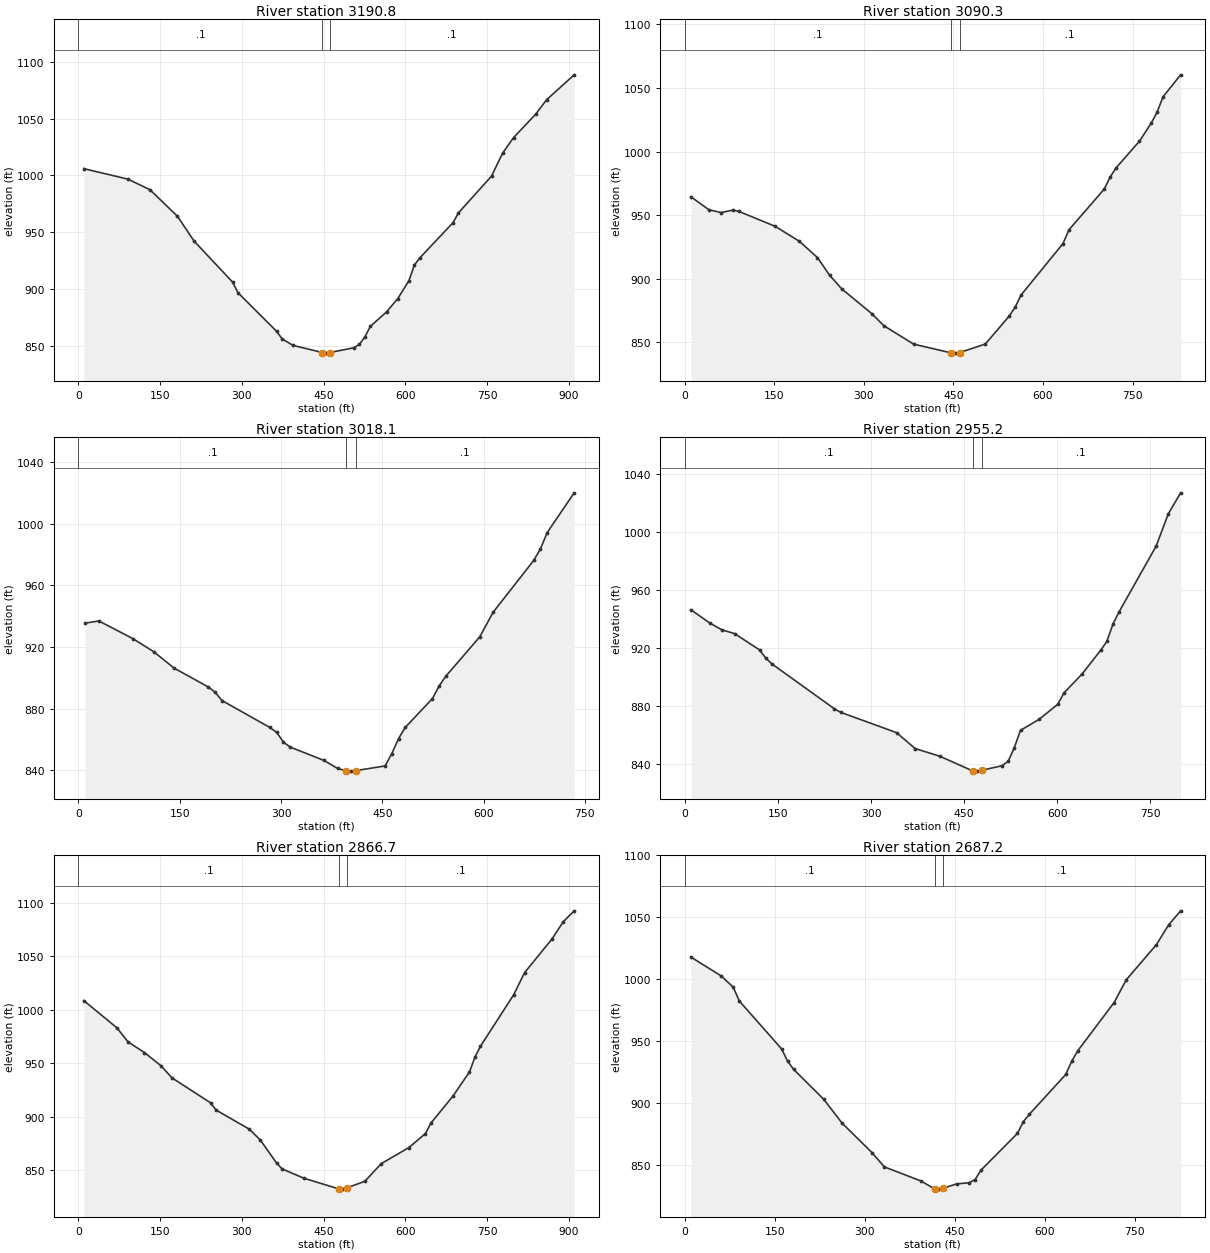
Type RM Length L Ch R = 1 ,3190.8  ,102.2,100.5,98.8
XS GIS Cut Line= 3
     1680733.209       201957.94     1680289.268      201858.232
     1679845.327      201758.525
#Sta/Elev= 30
    10.1 1005.93      91  996.71   131.4  987.38     182  963.95   212.3  942.19
   283.1  905.99   293.2  896.54     364  862.57   374.1  855.89   394.3   850.2
     448  843.95     455  843.42     462  843.97   505.6  848.13   515.7  851.06
   525.8  857.56   535.9  866.96   566.2  879.97   586.4  891.54   606.7  907.24
   616.8  921.08   626.9  927.38   687.6  958.33   697.7  967.02   758.3  999.31
   778.6  1019.5   798.8 1033.29   839.2 1053.82   859.4 1066.62     910 1088.59
#Mann= 3 , 0 , 0
       0      .1       0     448    .045       0     462      .1       0
Bank Sta=448,462
XS Rating Curve= 0 ,0
Exp/Cntr=0.3,0.1

Type RM Length L Ch R = 1 ,3090.3  ,72.4,72.1,71.9
XS GIS Cut Line= 4
     1680741.512       201889.98     1680438.433      201777.728
       1680111.3      201732.828     1679939.715      201689.531
#Sta/Elev= 30
    10.1  964.47    40.4  954.23    60.6  952.05    80.8  953.98    90.9  952.87
   151.5  941.19   191.9  929.41   222.2  916.64   242.4  902.81   262.6  892.14
   313.1  872.59   333.2  863.14   383.2  848.61   446.2   841.7   453.3  841.52
   460.3  841.99   503.3  848.65   543.3  870.64   553.3  877.68   563.3  887.28
   633.4  927.64   643.4  938.49   702.6  970.55   712.4  979.94   722.2  987.12
   761.5 1008.18   781.2 1022.37     791 1030.97   800.9 1042.99   830.4 1060.31
#Mann= 3 , 0 , 0
       0      .1       0   446.2    .045       0   460.3      .1       0
Bank Sta=446.2,460.3
XS Rating Curve= 0 ,0
Exp/Cntr=0.3,0.1

Type RM Length L Ch R = 1 ,3018.1  ,61.5,62.9,64.3
XS GIS Cut Line= 4
     1680696.812      201835.658     1680434.624      201703.362
     1680176.045      201670.889     1679999.248      201638.416
#Sta/Elev= 30
    10.1  935.51    30.4  936.91      81  925.37   111.4  916.99   141.8  906.25
   192.4  894.01   202.5  890.58   212.7  885.18   283.5  867.67   293.7  864.45
   303.7  858.08   313.7   854.9   363.8  846.23   383.9     841   396.9  839.47
   403.9  839.29     411  839.65   454.1  842.66   464.1  850.74   474.1  860.48
   484.1  867.79   524.2  886.45   534.2  894.75   544.3  901.14   594.2  926.56
   614.2   942.7   674.1  976.24   684.1   983.8   694.1  994.37     734 1020.22
#Mann= 3 , 0 , 0
       0      .1       0   396.9    .045       0     411      .1       0
Bank Sta=396.9,411
XS Rating Curve= 0 ,0
Exp/Cntr=0.3,0.1

Type RM Length L Ch R = 1 ,2955.2  ,88,88.5,89.1
XS GIS Cut Line= 4
     1680789.019      201729.821     1680457.075      201651.646
     1680192.481       201599.93     1680006.064      201575.876
#Sta/Elev= 30
      10  946.09    40.1  936.99    60.2  932.21    80.2  929.68   120.4  918.43
   130.4  912.78   140.4  908.76   240.7  877.91   250.8  875.45     341  861.41
     371  850.43   410.9  845.11   463.8  834.99   470.8  834.86   477.9   835.4
   510.8  838.57   520.8  841.61   530.7     851   540.7     863   570.7  870.55
   600.6  880.93   610.6  888.69   640.3  902.05     670  918.25   679.9  924.38
   689.8  936.46   699.7  944.87     759  989.86   778.8 1012.31   798.6 1026.74
#Mann= 3 , 0 , 0
       0      .1       0   463.8    .045       0   477.9      .1       0
Bank Sta=463.8,477.9
XS Rating Curve= 0 ,0
Exp/Cntr=0.3,0.1

Type RM Length L Ch R = 1 ,2866.7  ,180.2,179.5,178.9
XS GIS Cut Line= 3
     1680814.646      201644.955     1680370.624      201545.608
     1679926.603      201446.261
#Sta/Elev= 30
    10.1 1008.54    70.8   983.1      91  970.04   121.3  959.93   151.7  947.57
   171.9  936.22   242.7  912.88   252.8  906.09   313.4  888.34   333.7  878.27
     364  856.38   374.1  850.96   414.6  842.16   478.3  832.26   485.3  832.07
   492.4  833.15   525.8   839.4   556.1  855.98   606.7  870.99     637  884.06
   647.1  893.87   687.6  919.17   717.9  941.82     728  955.75   738.1  965.88
   798.8 1013.84     819 1034.73   869.6 1066.42   889.8  1082.3     910 1092.62
#Mann= 3 , 0 , 0
       0      .1       0   478.3    .045       0   492.4      .1       0
Bank Sta=478.3,492.4
XS Rating Curve= 0 ,0
Exp/Cntr=0.3,0.1

Type RM Length L Ch R = 1 ,2687.2  ,131.2,127.7,124.3
XS GIS Cut Line= 2
     1680799.643      201443.479     1679987.154      201289.534
#Sta/Elev= 30
    10.1 1017.76    60.5 1002.56    80.7  993.48    90.8  982.35   161.4  943.56
   171.4  933.69   181.5  927.03   231.9  902.75   262.2  883.66   312.6  859.54
   332.8  848.25   393.3  836.95   416.5  830.53   423.6  830.27   430.6  830.98
   453.8  834.53     474   835.4   484.1  837.98   494.1  845.69   554.7  875.27
   564.7  884.86   574.8  890.83   635.3  922.88   645.4  933.74   655.5  942.15
     716  981.04   736.2  999.36   786.6 1027.84   806.8  1043.7   826.9  1055.1
#Mann= 3 , 0 , 0
       0      .1       0   416.5    .045       0   430.6      .1       0
Bank Sta=416.5,430.6
XS Rating Curve= 0 ,0
Exp/Cntr=0.3,0.1

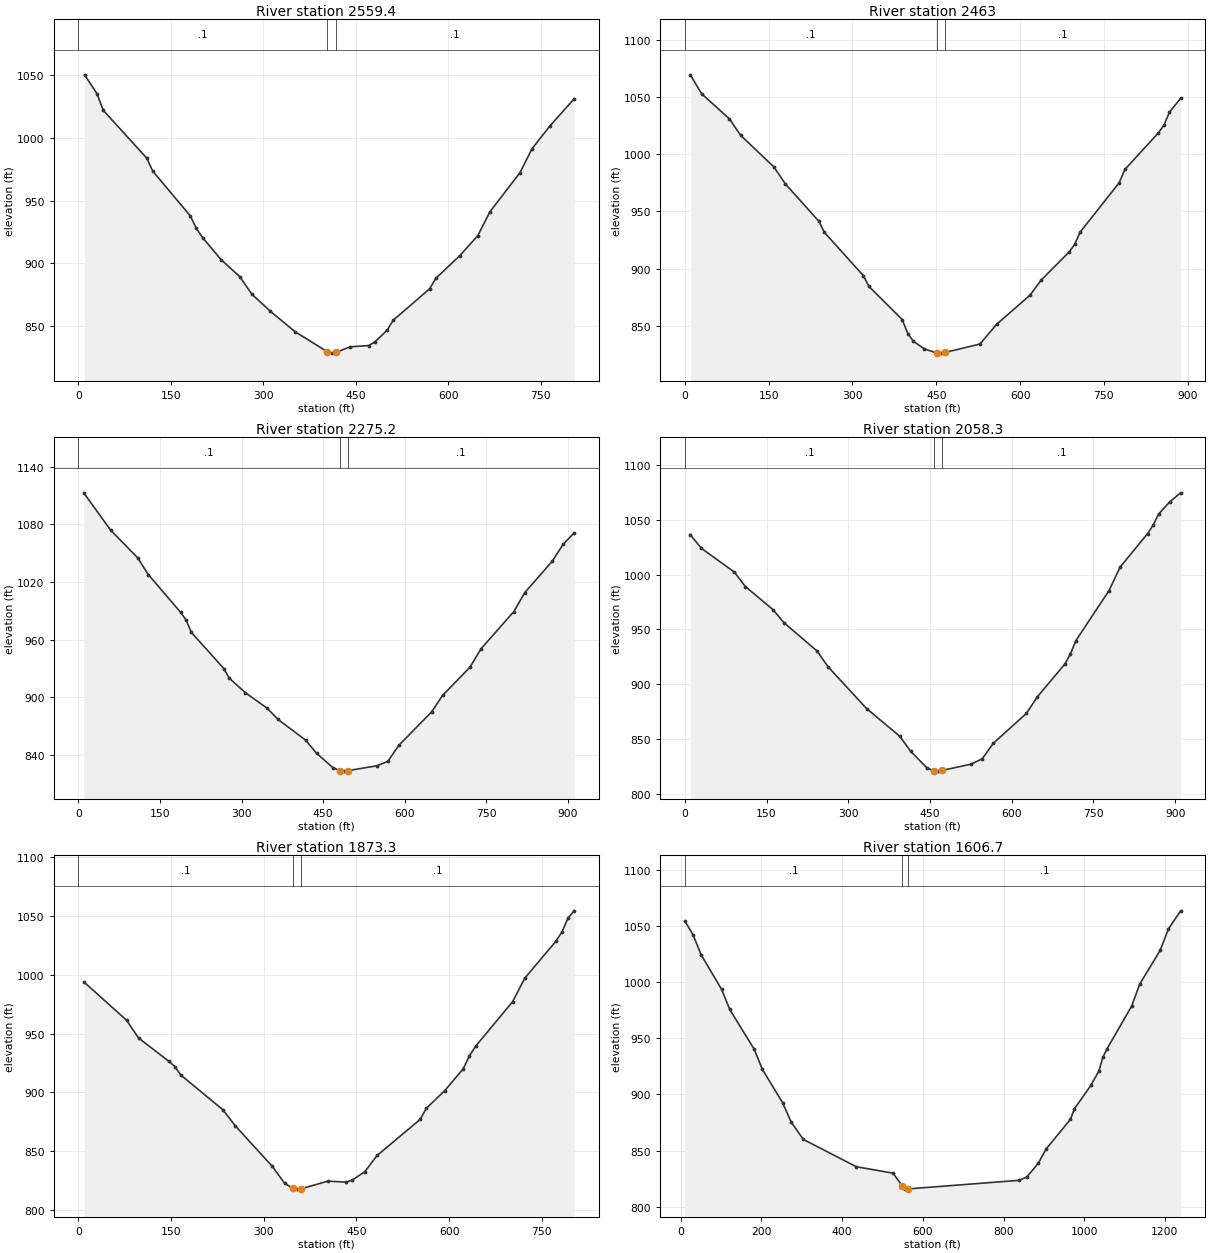
Type RM Length L Ch R = 1 ,2559.4  ,99.1,96.4,93.8
XS GIS Cut Line= 4
     1680810.467      201281.416      1680561.91      201241.326
     1680273.263      201236.515     1680010.273      201218.875
#Sta/Elev= 30
    10.1 1050.36    30.2 1035.42    40.3 1022.12   110.8  983.92   120.8  973.42
   181.3  937.91   191.3  927.93   201.4  920.49   231.6  902.75   261.7  889.32
   281.6  875.12   311.5  861.57   351.3  845.35   403.9  829.29     411   828.2
   418.2  828.83   440.9  833.25   470.8  834.23   480.7  837.11   500.6   846.4
   510.6  854.47   569.7  879.59   579.5   887.8   618.6  906.03   647.8  922.05
   667.4  941.04   716.2   972.3   735.7  991.38     765 1009.74     804 1031.24
#Mann= 3 , 0 , 0
       0      .1       0   403.9    .045       0   418.2      .1       0
Bank Sta=403.9,418.2
XS Rating Curve= 0 ,0
Exp/Cntr=0.3,0.1

Type RM Length L Ch R = 1 ,2463    ,186.6,187.8,189.1
XS GIS Cut Line= 4
      1680856.57       201115.41     1680527.299      201128.239
     1680270.723      201158.173     1679971.386       201149.62
#Sta/Elev= 30
      10 1069.22      30 1052.76    79.9 1030.79    99.9 1016.46   159.8  988.71
   179.7  974.21   239.7  941.62   249.6  931.94   319.5  894.05   329.5  884.66
   389.1  855.73   399.1  843.52     409  836.82   428.9  830.04   451.6  826.52
   458.7  826.44   465.8  826.99   528.2  834.39     558  851.63   617.8  876.98
   637.7  890.13   687.7  914.64   697.6  921.25   707.6  932.09   777.5   975.2
   787.5  986.67   847.4 1018.54   857.4 1025.34   867.3 1036.55   887.3 1048.77
#Mann= 3 , 0 , 0
       0      .1       0   451.6    .045       0   465.8      .1       0
Bank Sta=451.6,465.8
XS Rating Curve= 0 ,0
Exp/Cntr=0.3,0.1

Type RM Length L Ch R = 1 ,2275.2  ,215,216.9,218.8
XS GIS Cut Line= 3
     1680863.462      200895.385     1680550.818      200946.498
     1679957.325      200979.138
#Sta/Elev= 30
     9.9 1112.65    59.4 1073.77   108.9 1045.16   128.7 1027.57   188.1  988.22
     198   980.4   207.9  967.35   267.3  929.87   277.2  919.94   306.9  904.77
     347  888.57   367.2  876.85   417.5  855.45   437.7  841.75   467.9  826.74
   480.9  823.53   488.1  823.12   495.2   823.6   548.5  828.67   568.7  833.22
   588.8  849.81   649.3  884.83   669.4  901.87   719.8  931.32   739.9  950.31
   800.4  989.18   820.5 1008.89   870.9 1041.48     891 1059.16   911.2 1070.97
#Mann= 3 , 0 , 0
       0      .1       0   480.9    .045       0   495.2      .1       0
Bank Sta=480.9,495.2
XS Rating Curve= 0 ,0
Exp/Cntr=0.3,0.1

Type RM Length L Ch R = 1 ,2058.3  ,183.6,185,186.3
XS GIS Cut Line= 3
       1680826.1      200757.145     1680371.409      200739.283
     1679916.805      200721.331
#Sta/Elev= 30
    10.1 1036.47    30.3 1024.08      91 1002.33   111.2  989.12   161.8  968.09
     182  956.11   242.7  930.32   262.9  915.92   333.7  877.73   394.4  852.57
   414.6  838.76   444.9  823.33     458  820.84   465.2  820.66   472.3   821.3
   525.8   827.1     546  831.95   566.3  846.13   626.9  873.31   647.1  888.52
   697.7  918.53   707.8  927.68   717.9  939.87   778.6  985.48   798.8 1006.76
   849.3 1037.43   859.4 1044.94   869.6 1055.25   889.8  1066.3     910 1074.65
#Mann= 3 , 0 , 0
       0      .1       0     458    .045       0   472.3      .1       0
Bank Sta=458,472.3
XS Rating Curve= 0 ,0
Exp/Cntr=0.3,0.1

Type RM Length L Ch R = 1 ,1873.3  ,294.4,266.6,225.7
XS GIS Cut Line= 5
     1680717.859      200622.338     1680480.527      200566.212
     1680331.393      200550.176     1680271.058      200584.854
     1679938.512      200649.599
#Sta/Elev= 30
     9.8  993.47      78  961.35    97.6  946.17   146.3  926.54   156.1  922.02
   165.8  914.79   234.1  885.25   253.9  871.72   313.9  837.26   333.9   822.8
   346.7  818.83   353.9  817.92   361.1   818.3   403.8  824.71   433.6  823.85
   443.6   825.7   463.5  832.72   483.4  846.49   553.1  877.12   563.1  886.58
     593  901.61   622.9  920.19   632.9  931.09   642.8  939.24   702.6  977.02
   722.5   997.1   772.4 1028.21   782.3 1036.03   792.3 1048.01   802.3 1054.22
#Mann= 3 , 0 , 0
       0      .1       0   346.7    .045       0   361.1      .1       0
Bank Sta=346.7,361.1
XS Rating Curve= 0 ,0
Exp/Cntr=0.3,0.1

Type RM Length L Ch R = 1 ,1606.7  ,64,62.6,74.3
XS GIS Cut Line= 5
     1680777.529       200045.32     1680473.845      200052.761
     1680328.047      200536.886     1680232.571      200582.449
     1679913.657      200638.608
#Sta/Elev= 30
    10.1 1054.73    30.4 1042.53    50.6 1024.61   101.3  993.77   121.5  975.81
   182.3  940.23   202.5  922.29   253.1  892.27   273.4  875.63   303.8  859.91
   435.2  835.54   526.2  829.77   549.3  818.34   556.6  815.55   563.8  815.76
   838.2  823.38   857.5  826.29   886.3  838.67   905.5  851.33   965.8  877.75
   975.9  887.34  1016.4  907.99  1036.6  921.03  1046.7  933.52  1056.8  940.84
  1117.6  978.81  1137.8   998.6  1188.4 1028.57  1208.6 1047.51    1239 1063.79
#Mann= 3 , 0 , 0
    10.1      .1       0   549.3    .045       0   563.8      .1       0
#XS Ineff= 2 , 0
       0                     600       0
Permanent Ineff=
       F       F
Bank Sta=549.3,563.8
XS Rating Curve= 0 ,0
Exp/Cntr=0.3,0.1

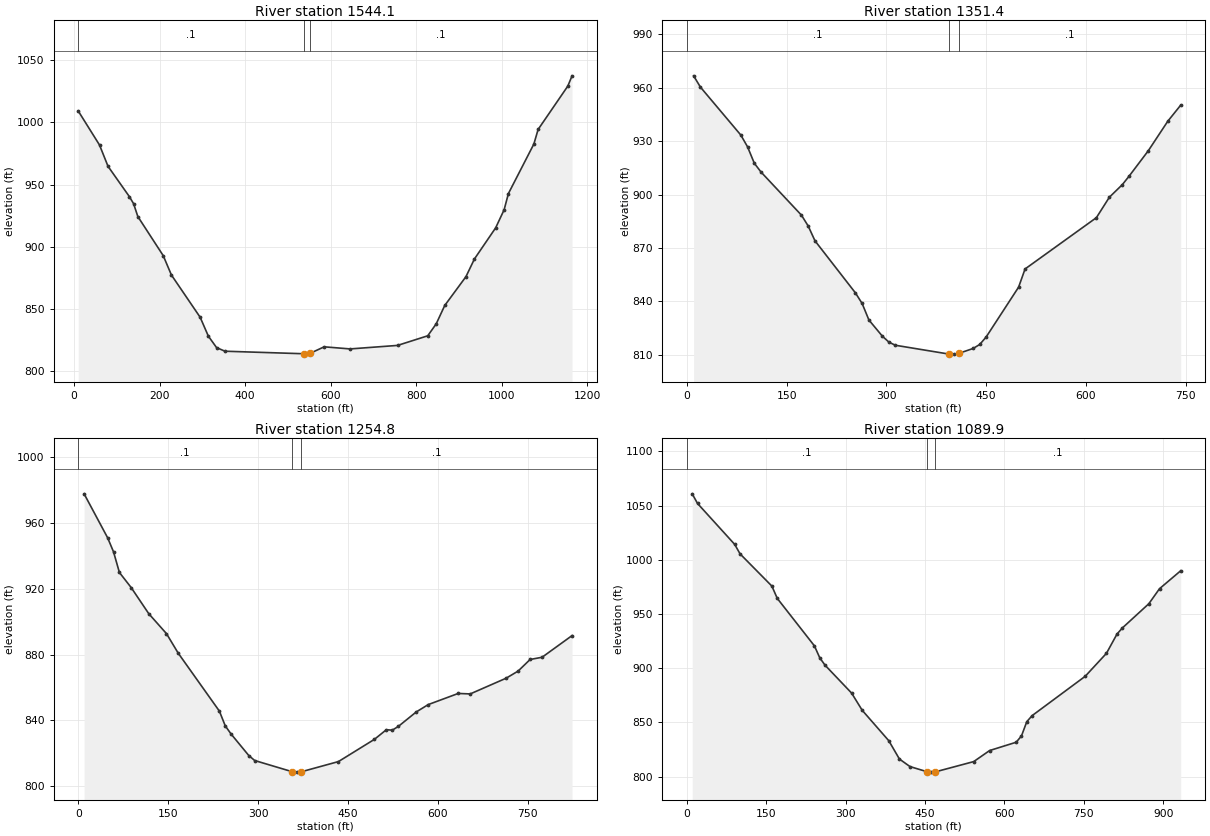
Type RM Length L Ch R = 1 ,1544.1  ,171.5,192.8,213.9
XS GIS Cut Line= 5
     1680716.055      199943.817     1680532.043      200019.587
     1680397.341        200070.1     1680277.806      200539.052
      1679942.12      200571.123
#Sta/Elev= 30
      10 1009.25    59.7  981.94    79.6  964.81   129.4  940.51   139.3  934.81
   149.3  924.44   208.6  893.04   227.8  877.45   294.9  843.54   314.1  828.35
   333.3  819.15   352.9  816.25   537.2  814.21   544.5  813.91   551.8  814.56
   584.8  819.78   645.3  818.09   756.2  820.91   826.8  828.64   846.6  838.26
   866.5     853   916.1  876.16   935.9  890.37   985.5  915.37  1005.3  929.92
  1015.3  942.92  1074.8  982.72  1084.7  994.41  1154.1 1029.24    1164 1037.49
#Mann= 3 , 0 , 0
      10      .1       0   537.2    .045       0   551.8      .1       0
#XS Ineff= 2 , 0
       0     525             555       0
Permanent Ineff=
       F       F
Bank Sta=537.2,551.8
XS Rating Curve= 0 ,0
Exp/Cntr=0.3,0.1

Type RM Length L Ch R = 1 ,1351.4  ,93.1,96.6,100.1
XS GIS Cut Line= 4
     1680660.731       199900.52     1680408.165      200050.857
     1680202.504      200112.195     1680093.059      200319.058
#Sta/Elev= 30
    10.1  966.74    20.3  960.42    81.1  933.45    91.2  926.85   101.4   917.6
   111.5  912.67   172.3  888.44   182.4  882.36   192.6  874.05   253.4   844.8
   263.5  838.84   273.7  829.56   293.9  820.49   303.7  817.15   313.4  815.38
   393.9  810.43   401.2  810.39   408.5  810.76   430.5  813.58   440.3  815.81
     450  820.01   498.8  848.02   508.5  858.23   615.8  887.06   635.3  898.54
   654.8  905.61   664.6   910.2   693.8  924.63   723.1  941.21   742.6  950.28
#Mann= 3 , 0 , 0
       0      .1       0   393.9    .045       0   408.5      .1       0
Bank Sta=393.9,408.5
XS Rating Curve= 0 ,0
Exp/Cntr=0.3,0.1

Type RM Length L Ch R = 1 ,1254.8  ,170.9,164.9,158.9
XS GIS Cut Line= 5
     1680626.321      199814.394     1680409.368      199948.628
      1680380.52      199975.223     1680192.281      199998.273
     1679972.054      200256.986
#Sta/Elev= 30
     9.8  977.84    49.1  951.06    58.9  942.52    68.7  929.99    88.3  920.83
   117.7  904.91   147.2   892.8   166.8  880.91   235.5  845.64   245.3  836.66
   255.1  831.67   284.5  818.65   294.4   815.6   356.9   808.8   364.2  808.54
   371.5  808.69   434.1  814.96     494  828.46     514  834.32     524  834.08
     534  836.35   563.9  845.15   583.9  849.63   633.9   856.4   653.9  856.11
   713.8  865.67   733.8     870   753.8  877.06   773.8  878.42   823.8   891.6
#Mann= 3 , 0 , 0
       0      .1       0   356.9    .045       0   371.5      .1       0
Bank Sta=356.9,371.5
XS Rating Curve= 0 ,0
Exp/Cntr=0.3,0.1

Type RM Length L Ch R = 1 ,1089.9  ,157,153.4,149.9
XS GIS Cut Line= 3
     1680727.567      199740.182     1680359.055      199787.133
     1679846.364       200016.67
#Sta/Elev= 30
      10 1060.91    20.1 1052.01    90.4  1014.2   100.4 1005.53   160.6  975.75
   170.7  964.46     241  920.58     251  909.64     261   902.8   311.2  877.06
   331.3  861.14   381.5  833.08   401.6  816.17   421.6   809.2   454.4  804.38
   461.8  804.09   469.1  804.28     542  813.81   572.1  824.02   622.3  831.68
   632.3  837.54   642.3  850.64   652.4  856.24   752.7  892.53   792.8   913.7
   812.8  931.51   822.9  937.13     873  959.52   893.1  973.34   933.2  989.94
#Mann= 3 , 0 , 0
       0      .1       0   454.4    .045       0   469.1      .1       0
Bank Sta=454.4,469.1
XS Rating Curve= 0 ,0
Exp/Cntr=0.3,0.1