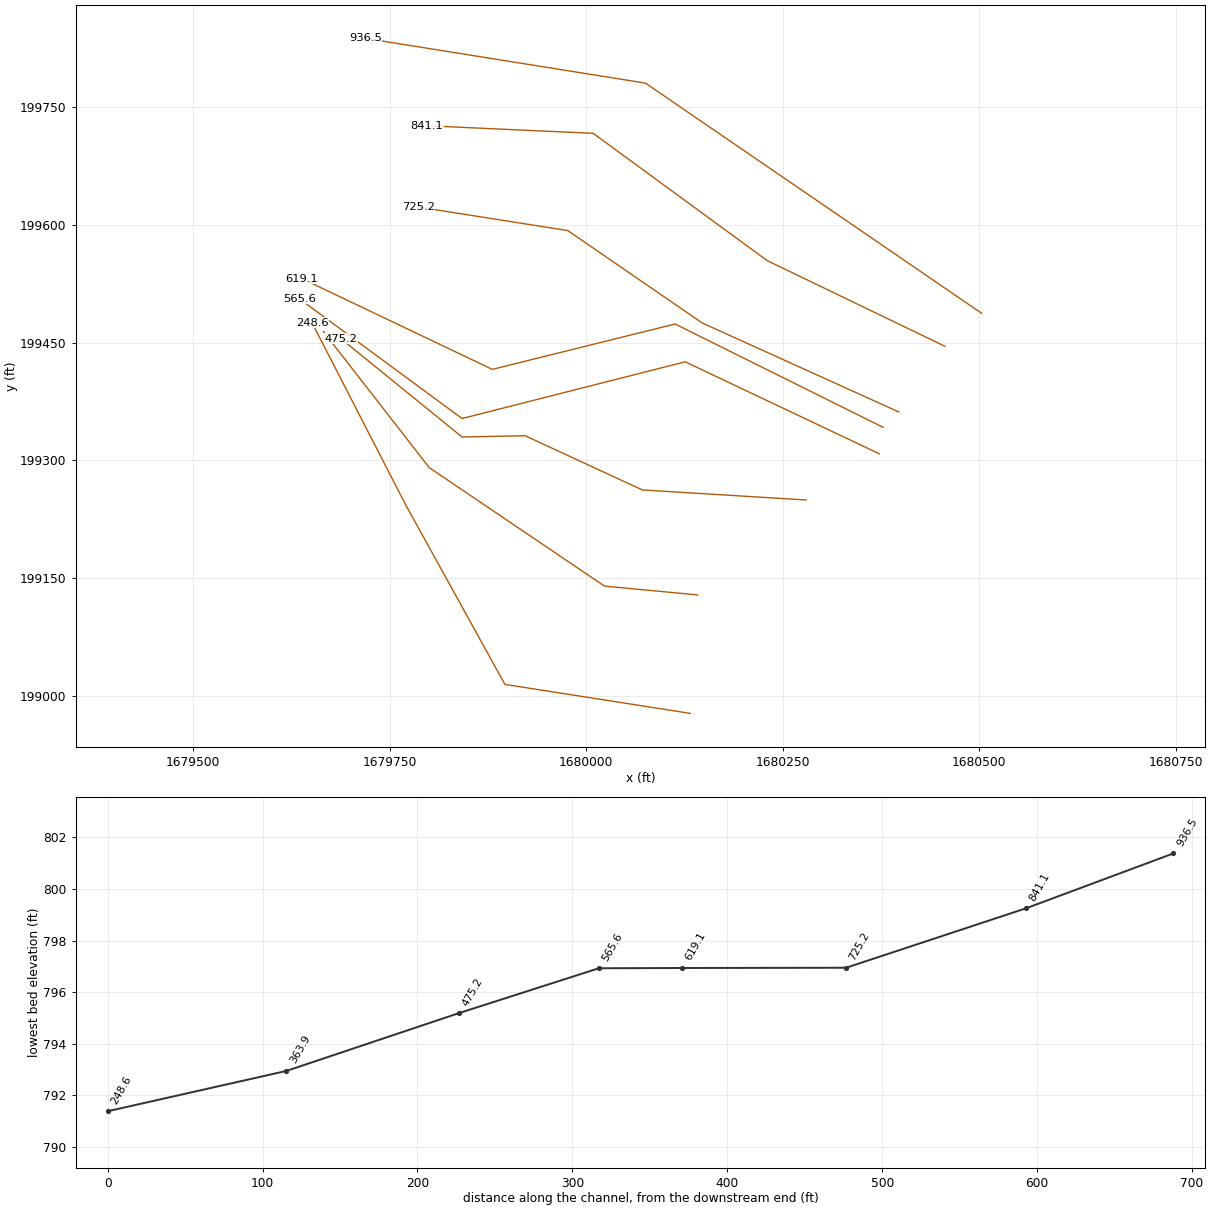
HEC-RAS study lmcrk.prj: lmcrk

--- lmcrk.g01 (geometry) --- (continued)

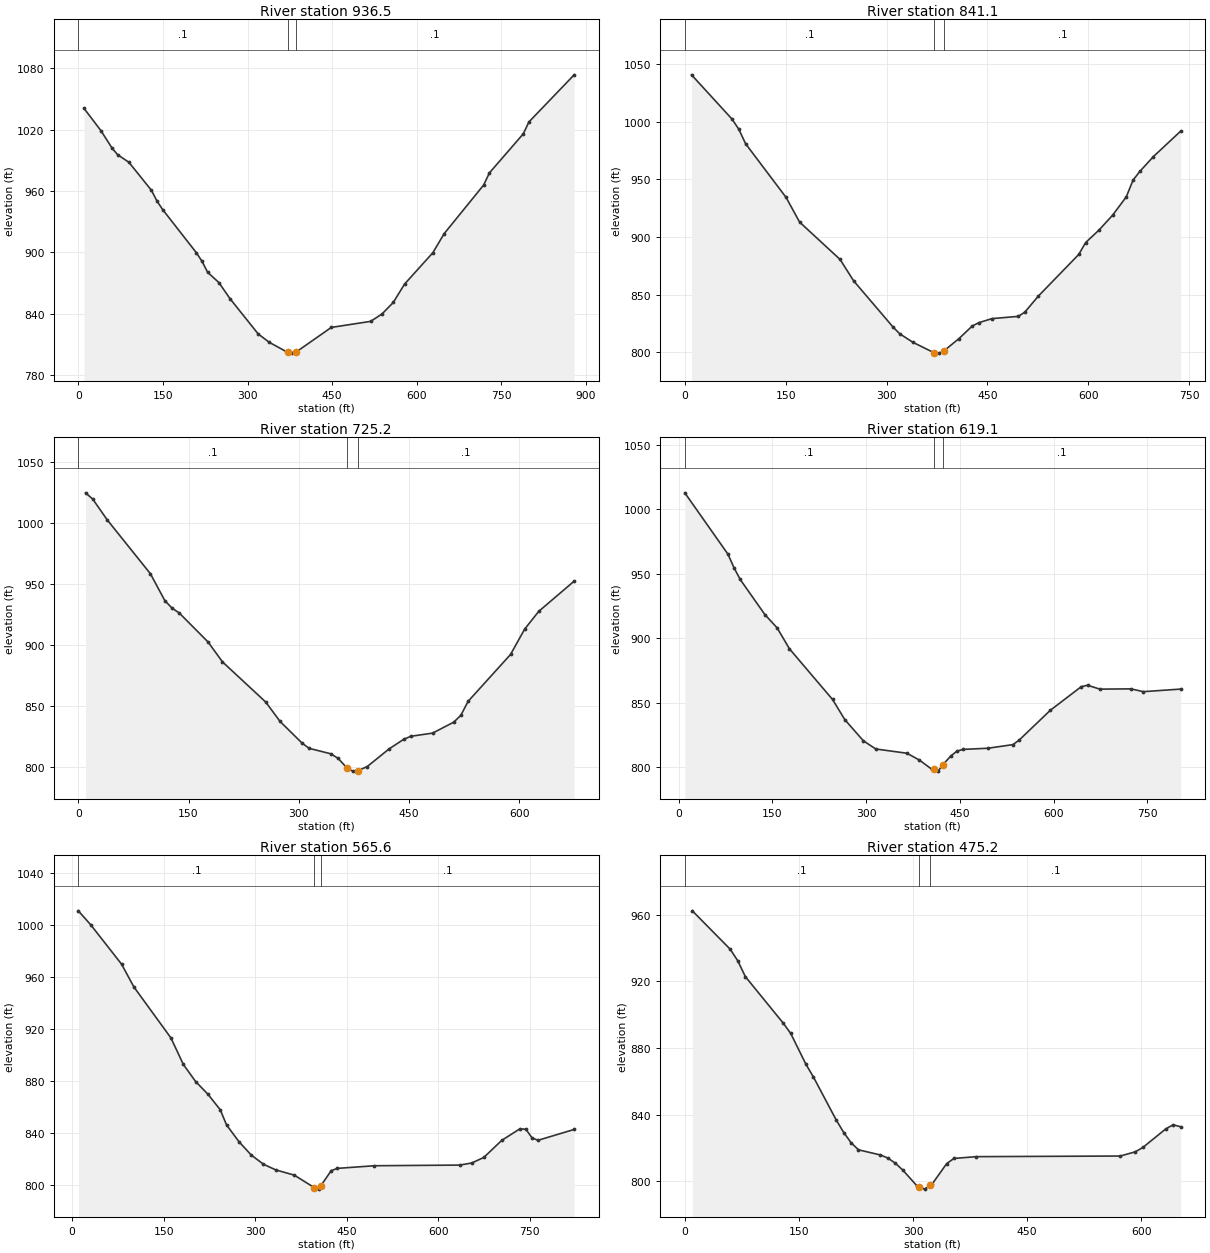
Type RM Length L Ch R = 1 ,936.5   ,96,95.3,94.7
XS GIS Cut Line= 3
     1680502.844       199487.26     1680075.218      199780.184
     1679718.844      199837.179
#Sta/Elev= 30
      10 1040.77    39.9 1019.08    59.8 1001.87    69.8  995.34    89.7  988.01
   129.6  960.61   139.6  949.95   149.5   941.8   209.3  899.56   219.3   891.2
   229.3  880.44   249.2   870.4   269.1  854.53     319  820.11   338.9  811.83
   371.4  802.09   378.8  801.38   386.1  802.43   448.6  826.53   518.3  832.44
   538.4  839.63   558.4   850.9   578.5  868.91   628.6  899.54   648.7  918.23
   718.8  965.83   728.9  977.61     789 1015.84     799 1027.48   879.2 1073.53
#Mann= 3 , 0 , 0
       0      .1       0   371.4    .045       0   386.1      .1       0
Bank Sta=371.4,386.1
XS Rating Curve= 0 ,0
Exp/Cntr=0.3,0.1

Type RM Length L Ch R = 1 ,841.1   ,115.4,116,116.5
XS GIS Cut Line= 4
     1680456.072        199445.3     1680229.965      199554.344
     1680008.669      199716.307     1679796.995      199725.929
#Sta/Elev= 30
      10 1040.62    70.3 1002.18    80.3  993.41    90.4  980.86   150.6  934.29
   170.7  912.89   230.9  880.47     251  861.97   309.8  821.76   319.6  816.02
   339.2  808.63     371  799.46   378.4  799.25   385.7  801.41   407.7  811.88
   427.3  822.74   437.1  825.64   456.7  829.18   495.9  831.14   505.7  834.87
   525.3   848.5   585.8  884.88   595.9  895.11   616.1  906.12   636.3  919.05
   656.4  934.79   666.5  949.33   676.6  956.88   696.8  969.75   737.2  991.75
#Mann= 3 , 0 , 0
       0      .1       0     371    .045       0   385.7      .1       0
Bank Sta=371,385.7
XS Rating Curve= 0 ,0
Exp/Cntr=0.3,0.1

Type RM Length L Ch R = 1 ,725.2   ,87.2,106.1,123.9
XS GIS Cut Line= 4
     1680397.541      199361.645      1680147.38      199474.966
      1679976.33      199592.563     1679786.037      199622.497
#Sta/Elev= 30
     9.8  1025.1    19.6 1019.99    39.2 1003.02    98.1  958.77   117.7  936.76
   127.5  930.59   137.3  926.62   176.5  902.87   196.2   886.5     255  853.61
   274.6  837.66   304.3  820.04   314.2  815.61   343.8  811.14   353.7  807.33
   366.1  799.22   373.5  796.95   380.9   797.4   393.2  800.71   422.9  815.16
   442.7  822.99   452.6  825.53   482.2  828.12   511.1  837.16   520.7  842.82
   530.4  854.12   588.2  892.57   607.4  913.35   626.7  927.99   674.8   952.7
#Mann= 3 , 0 , 0
       0      .1       0   366.1    .045       0   380.9      .1       0
Bank Sta=366.1,380.9
XS Rating Curve= 0 ,0
Exp/Cntr=0.3,0.1

Type RM Length L Ch R = 1 ,619.1   ,55.2,53.5,52.9
XS GIS Cut Line= 4
     1680377.496      199342.135     1680112.903       199473.63
     1679880.382        199415.9     1679638.239      199531.359
#Sta/Elev= 30
     9.8 1012.72    78.8  965.19    88.6  954.59    98.5  945.52   137.9  918.37
   157.6  907.99   177.3  891.78   246.2  852.52   265.9  836.86   295.5  820.48
   315.4  814.12   365.3  810.81   385.3   805.5   405.3  798.34   407.9  798.34
   415.3  796.94   422.7  801.89   435.2  808.53   445.2  812.43   455.2  813.78
   495.1   814.7     535   817.5     545  821.06   594.7  844.09   644.3  862.43
   654.3  863.52   674.1  860.52   723.8  860.72   743.7  858.56   803.3  860.55
#Mann= 3 , 0 , 0
     9.8      .1       0   407.9    .045       0   422.7      .1       0
Bank Sta=407.9,422.7
XS Rating Curve= 0 ,0
Exp/Cntr=0.3,0.1

Type RM Length L Ch R = 1 ,565.6   ,104.1,90.4,76.5
XS GIS Cut Line= 4
     1680372.685      199308.459     1680125.732      199425.522
     1679841.895       199353.36     1679635.032      199505.702
#Sta/Elev= 30
    10.1 1011.16    30.4 1000.42      81   970.1   101.2  952.56     162  913.27
   182.2  892.97   202.4  879.76   222.7  869.95   242.9  857.95   253.1  846.36
   273.3  833.56   293.5  823.21   313.7  816.08   333.9  811.73   364.2   807.7
   397.2  798.05   404.6  796.93     408 799.714   424.8  811.17   434.9  812.91
   495.5  814.93   635.3  815.44   655.1  817.04   674.9   821.3   704.5  834.51
   734.1  843.35     744     843   753.9  836.46   763.8  834.52   823.1  842.87
#Mann= 3 , 0 , 0
    10.1      .1       0   397.2    .045       0     408      .1       0
#XS Ineff= 2 , 0
       0     385             410       0
Permanent Ineff=
       F       F
Bank Sta=397.2,408
XS Rating Curve= 0 ,0
Exp/Cntr=0.3,0.1

Type RM Length L Ch R = 1 ,475.2   ,114.6,111.4,108.2
XS GIS Cut Line= 5
     1680279.677      199249.661      1680071.21       199262.49
     1679922.075      199331.444     1679841.895      199329.841
      1679687.95      199454.921
#Sta/Elev= 30
     9.9   962.3    59.7  939.24    69.6  932.32    79.6  922.79   129.3  894.91
   139.2   888.7   159.1  870.25   169.1  862.49   198.9   836.8   208.9  829.19
   218.5   823.1   228.2  818.81   257.2  815.69   266.9  813.85   276.5  810.84
   286.2  806.78   305.5  796.98   307.7  796.57   315.2  795.19   322.6  797.39
   324.8  798.05   344.2  810.51   353.8  813.63   383.2  814.69   572.4  815.07
   592.2   817.6   602.1  820.22   631.9  831.26   641.8  833.84   651.7  832.64
#Mann= 3 , 0 , 0
       0      .1       0   307.7    .045       0   322.6      .1       0
Bank Sta=307.7,322.6
XS Rating Curve= 0 ,0
Exp/Cntr=0.3,0.1

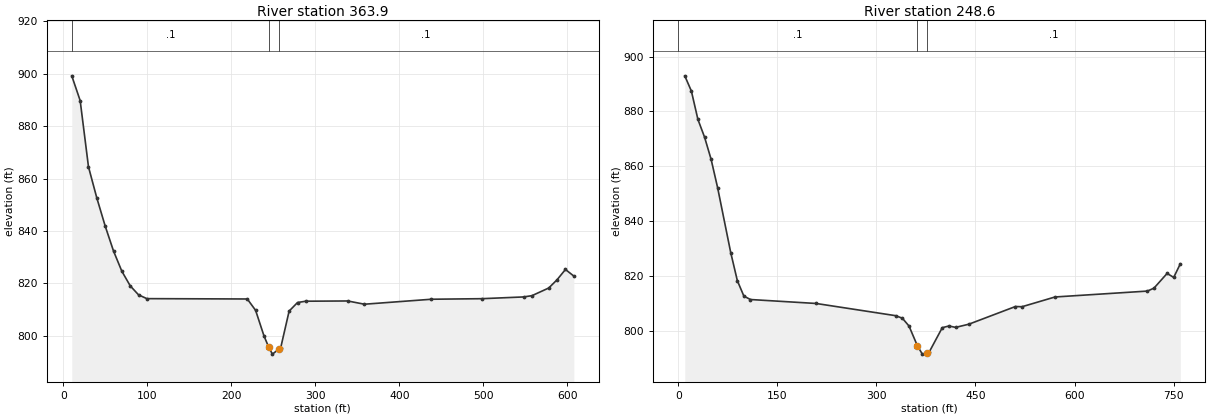
Type RM Length L Ch R = 1 ,363.9   ,124.7,115.3,105.8
XS GIS Cut Line= 4
     1680141.768      199128.857     1680023.102      199140.082
     1679800.202       199290.82       1679665.5      199464.008
#Sta/Elev= 30
     9.9  899.23    19.9  889.76    29.8  864.47    39.7  852.61    49.7  841.85
    59.6  832.33    69.5  824.62    79.5  819.03    89.4  815.59    99.3  814.14
   218.9  814.01   228.8  809.66   238.8  799.88  244.44  795.57   248.8  792.95
   256.2  794.79   258.7  795.42   268.7  809.39   278.7  812.66   288.6  813.16
   338.4  813.25   358.4  812.01   438.1  813.91     498  814.12   547.8  814.79
   557.8  815.27   577.8   818.2   587.7  821.34   597.7  825.28   607.7  822.75
#Mann= 3 , 0 , 0
     9.9      .1       0  244.44    .045       0   256.2      .1       0
Bank Sta=244.44,256.2
XS Rating Curve= 0 ,0
Exp/Cntr=0.3,0.1

Type RM Length L Ch R = 1 ,248.6   ,254,248.6,243.2
XS GIS Cut Line= 4
     1680132.146      198978.119     1679896.418      199015.002
     1679769.734      199244.316     1679651.068      199475.233
#Sta/Elev= 30
     9.9  892.97    19.9  887.41    29.8  877.05    39.8  870.62    49.7  862.56
    59.6  852.17    79.5  828.43    89.5   818.2    99.4  812.56   109.4  811.32
   208.8  809.88   329.3  805.42   339.4  804.49   349.4  801.65   362.1  794.44
   369.6  791.39     377  791.85   379.7  792.02   399.8  801.05   409.9  801.66
     420  801.15   440.1  802.32   510.6  808.77   520.5  808.69   570.5  812.25
   710.3   814.4   720.3  815.47   740.2  820.84   750.2  819.39   760.2  824.35
#Mann= 3 , 0 , 0
       0      .1       0   362.1    .045       0     377      .1       0
Bank Sta=362.1,377
XS Rating Curve= 0 ,0
Exp/Cntr=0.3,0.1
Stream Node=lmcrk           ,Main            , 0 , 0 ,Upstream end
Stream Node=lmcrk           ,Main            , 0 , 1 ,Downstream end

Chan Stop Cuts=-1
Use User Specified Reach Order=0